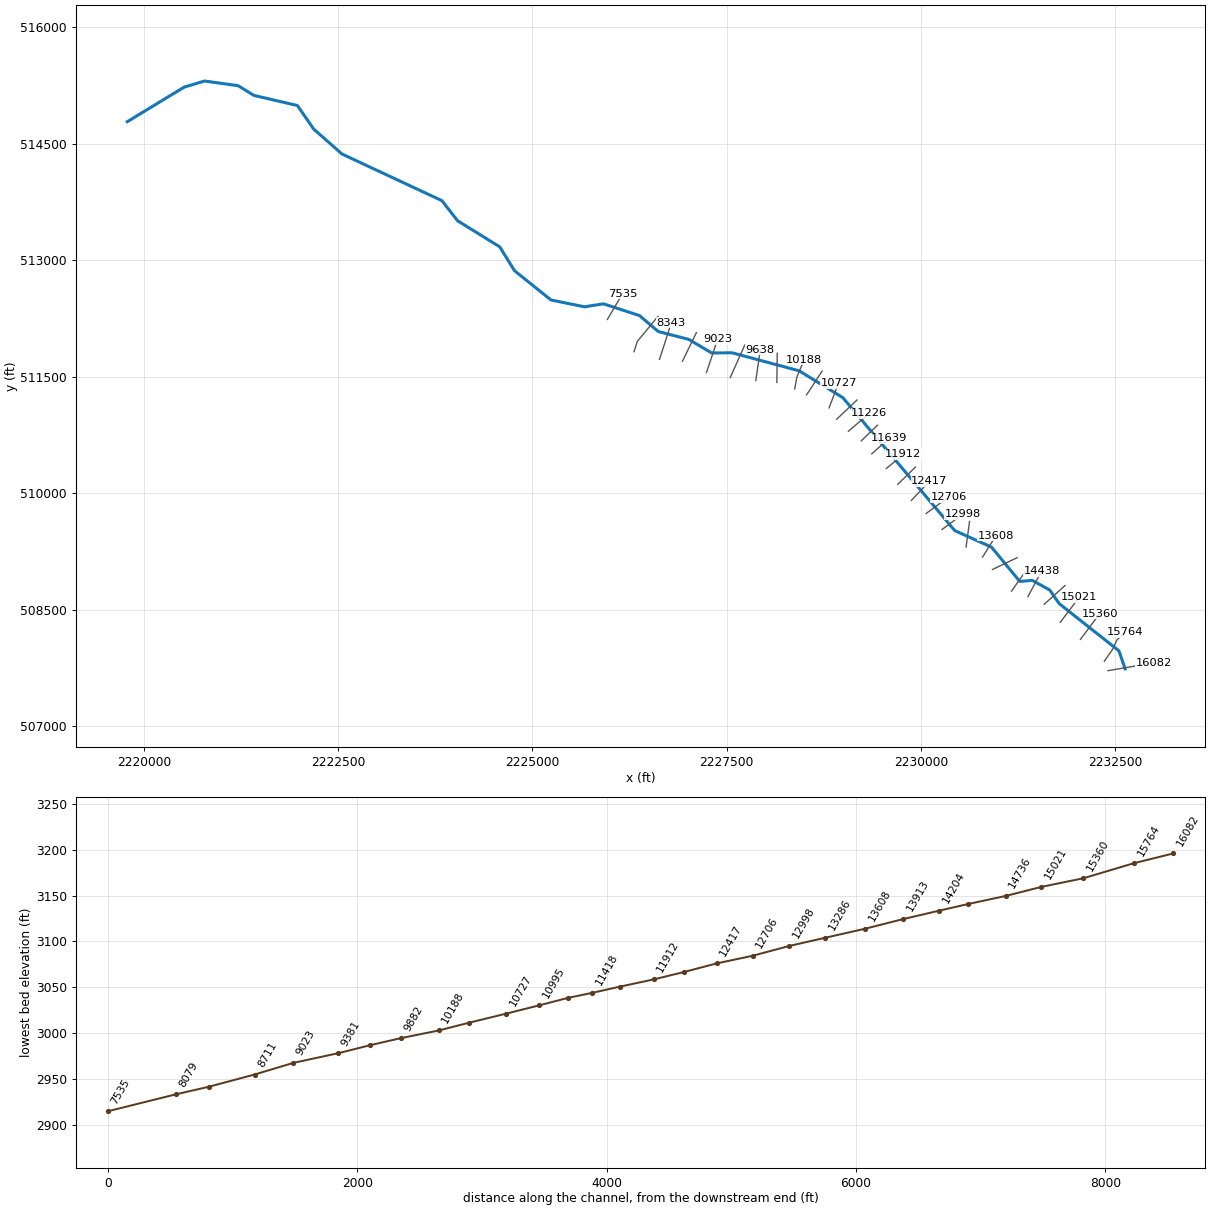
--- SLTYFK.prj (project) ---

Proj Title=SLTYFK
Current Plan=p01
Default Exp/Contr=0,0
English Units
Geom File=g01
Flow File=f01
Plan File=p01
Background Map Layer=Inundation Boundary (01pct Value_0)
Background Map Layer=Inundation Boundary (01pct Value_0)
Background Map Layer=Inundation Boundary (01pct Value_0)
BEGIN DESCRIPTION:
----------MODEL BY WOOD PLC 2021----------
Stream Name: Slaty Fork
Flood Zone: Enhanced Approximate
Pocahontas County, WV
HEC-RAS Version: RAS 6.1
Vertical Datum: NAVD88
Projection: NAD 1983 StatePlane West Virginia S FIPS 4702 (US Feet)
Terrain: 1-meter LIDAR (FEMA Region III 3DEP collected 2016-2018)
Land Use: 2019 NLCD
Hydrologic Method:
WV SIR2010-5033 regression equations
Model Notes:
Normal Depth tie in to Old Field Fork
END DESCRIPTION:
DSS Export Rating Curves= 0
DSS Export Rating Curve Sorted= 0
DSS Export Volume Flow Curves= 0
DXF OffsetX= 0
DXF OffsetY= 0
DXF ScaleX= 0
DXF ScaleY= 0

--- SLTYFK.p01 (plan) ---

Plan Title=Floodplain
Program Version=6.00
Short Identifier=Floodplain
Geom File=g01
Flow File=f01
Subcritical Flow
K Sum by GR= 0
Std Step Tol= 0.01
Critical Tol= 0.01
Num of Std Step Trials= 20
Max Error Tol= 0.3
Flow Tol Ratio= 0.001
Split Flow NTrial= 30
Split Flow Tol= 0.02
Split Flow Ratio= 0.02
Log Output Level= 0
Friction Slope Method= 1
Unsteady Friction Slope Method= 2
Unsteady Bridges Friction Slope Method= 1
Parabolic Critical Depth
Global Vel Dist= 0 , 0 , 0
Global Log Level= 0
CheckData=False
Encroach Param=-1 ,0,0, 0
Mapping Interval=1HOUR
Computation Time Step Use Courant=        0
Computation Time Step Use Time Series=    0
Computation Time Step Count To Double=0
Computation Time Step Max Doubling=0
Computation Time Step Max Halving=0
Computation Time Step Residence Courant=0
Run HTab= 0
Run UNet= 0
Run Sediment= 0
Run PostProcess= 0
Run WQNet= 0
Run RASMapper=-1
UNET Theta= 0
UNET Theta Warmup= 0
UNET ZTol= 0
UNET ZSATol= 0
UNET MxIter= 0
UNET Max Iter WO Improvement= 0
UNET MaxInSteps= 0
UNET DtIC= 0
UNET DtMin= 0
UNET MaxCRTS= 0
UNET WFStab= 0
UNET SFStab= 0
UNET WFX= 1
UNET SFX= 1
UNET Gravity=32.174
UNET 1D Methodology=Finite Difference
UNET DSS MLevel= 1
UNET Pardiso=0
UNET DZMax Abort= 0
UNET Use Existing IB Tables= 0
UNET Froude Reduction=False
UNET Froude Limit= 0
UNET Froude Power= 0
UNET D1 Cores= 0
UNET WindReference=Eulerian
UNET WindDragFormulation=Hsu (1988)
UNET D2 Coriolis=0
UNET D2 Cores= 0
UNET D2 Theta= 1
UNET D2 Theta Warmup= 1
UNET D2 Z Tol= 0.01
UNET D2 Volume Tol= 0.01
UNET D2 Max Iterations= 20
UNET D2 Equation= 0
UNET D2 RampUpFraction=0.1
UNET D2 TimeSlices= 1
UNET D2 Turbulence Formulation=Non-Conservative (original)
UNET D2 Eddy Viscosity=0.3
UNET D2 Transverse Eddy Viscosity=0.1
UNET D2 Smagorinsky Mixing=0
UNET D2 BCVolumeCheck=0
UNET D2 Cores=0
UNET D2 SolverType=PARDISO (Direct)
UNET D2 Minimum Iterations= 2147483647
UNET D2 Maximum Iterations= 2147483647
UNET D2 Restart Number= 10
UNET D2 Relaxation Coeff=1.3
UNET D2 SOR Precondition Iterations= 10
UNET D2 ILUT Maximum Fill= 8
UNET D2 ILUT Tolerance=1E-08
UNET D1D2 MaxIter= 0
UNET D1D2 ZTol=0.01
UNET D1D2 QTol=0.1
UNET D1D2 MinQTol=1
Write IC File= 0
Write IC File at Fixed DateTime=0
Write IC File at Sim End=0
Echo Input=False
Echo Parameters=False
Echo Output=False
Write Detailed= 0
HDF Write Warmup=0
HDF Write Time Slices=0
HDF Flush=0
HDF Compression= 1
HDF Chunk Size= 1
HDF Spatial Parts= 1
HDF Use Max Rows=0
HDF Fixed Rows= 1
Calibration Method= 0
Calibration Iterations= 20
Calibration Max Change=0.05
Calibration Tolerance=0.2
Calibration Maximum=1.5
Calibration Minimum=0.5
Calibration Optimization Method= 1
WQ AD Non Conservative
WQ ULTIMATE=-1
WQ Max Comp Step=1HOUR
WQ Output Interval=15MIN
WQ Output Selected Increments= 0
WQ Output face flow=0
WQ Output face velocity=0
WQ Output face area=0
WQ Output face dispersion=0
WQ Output cell volume=0
WQ Output cell surface area=0
WQ Output cell continuity=0
WQ Output cumulative cell continuity=0
WQ Output face conc=0
WQ Output face dconc_dx=0
WQ Output face courant=0
WQ Output face peclet=0
WQ Output face adv mass=0
WQ Output face disp mass=0
WQ Output cell mass=0
WQ Output cell source sink temp=0
WQ Output nsm pathways=0
WQ Output nsm derived pathways=0
WQ Create Restart=0
WQ Fixed Restart=0
WQ System Summary=0
WQ Write To DSS=0
Sorting and Armoring Iterations= 10
XS Update Threshold= 0.02
Bed Roughness Predictor= 0
Hydraulics Update Threshold= 0.02
Energy Slope Method= 1
Volume Change Method= 1
Sediment Retention Method= 0
Sediment TS Multiplier= 1
Warm Up Method= 0
XS Weighting Method= 0
Number of US Weighted Cross Sections= 1
Number of DS Weighted Cross Sections= 1
Upstream XS Weight=0
Main XS Weight=1
Downstream XS Weight=0
Number of DS XS's Weighted with US Boundary= 1
Upstream Boundary Weight= 1
Weight of XSs Associated with US Boundary= 0
Number of US XS's Weighted with DS Boundary= 1
Downstream Boundary Weight= 0.5
Weight of XSs Associated with DS Boundary= 0.5
Percentile Method= 0
Sediment Output Level= 3
Mass or Volume Output= 0
Output Increment Type= 1
Profile and TS Output Increment= 1
Transport Output Increment 1
XS Output Flag= 0
XS Output Increment= 10
Read HDF5 Sediment Hotstart= 0
Sediment Hotstart Type= 0
Write Gradation File= 0
Read Gradation Hotstart= 0
Write HDF5 File= 1
Write Binary Output= 1
Write DSS Sediment File= 0
DSS Sediment Output Type= 1
SV Curve= 0
Specific Gage Flag= 0
Subcell Erosion Methods= 0
Subcell Deposition Methods= 0
Advection Scheme= 1
Matrix Solver= 0
Implicit Weighting Factor= 1
Maximum Outer Loop Convergence Iterations= 5
Convergence Maximum Absolute= 0.001
Convergence RMSE= 0.0001
Grain Fractions Max Abs Error= 0.001
Max Subgrid Regions= 1
Max Subgrid Length Scale= 3.402823E+38
Initial Layer Thickness= 3.402823E+38
Min Layer Thickness= 3.402823E+38
Max Layer Thickness= 3.402823E+38
Number of Layers= 5

--- SLTYFK.f01 (steady flow) ---

Flow Title=Flow
Program Version=6.00
Number of Profiles= 6
Profile Names=01pct,10pct,04pct,02pct,0_2pct,01plus
River Rch & RM=SLTYFK,Main,16082
     607     322     427     514     847     898
River Rch & RM=SLTYFK,Main,13286
     719     384     508     610    1000    1060
River Rch & RM=SLTYFK,Main,10995
     804     430     569     682    1120    1190
River Rch & RM=SLTYFK,Main,7305
     953     514     677     810    1320    1410
River Rch & RM=SLTYFK,Main,6074
    1060     572     752     900    1460    1560
Boundary for River Rch & Prof#=SLTYFK,Main            , 1
Up Type= 0
Dn Type= 3
Dn Slope=0.01661
Boundary for River Rch & Prof#=SLTYFK,Main            , 2
Up Type= 0
Dn Type= 3
Dn Slope=0.01661
Boundary for River Rch & Prof#=SLTYFK,Main            , 3
Up Type= 0
Dn Type= 3
Dn Slope=0.01661
Boundary for River Rch & Prof#=SLTYFK,Main            , 4
Up Type= 0
Dn Type= 3
Dn Slope=0.01661
Boundary for River Rch & Prof#=SLTYFK,Main            , 5
Up Type= 0
Dn Type= 3
Dn Slope=0.01661
Boundary for River Rch & Prof#=SLTYFK,Main            , 6
Up Type= 0
Dn Type= 3
Dn Slope=0.01661
DSS Import GetInterval= 0
DSS Import GetPeak= 0
DSS Import FillOption= 0

--- SLTYFK.g01 (geometry) ---

Geom Title=Geometry
Program Version=6.10

River Reach=SLTYFK          ,Main
Reach XY= 30
     2232626.866      507739.904     2232547.055      507972.604
     2231777.312      508580.9282231657.74511793508755.249774503
     2231430.904       508879.812231271.20119213508865.823847053
     2230907.554      509307.658     2230433.949      509520.934
2228993.61808142511233.148570754     2228431.993      511578.248
2227569.35313764 511810.26707957     2227306.542      511808.065
     2227011.972       511982.66 2226619.6573974512083.917671389
     2226376.757      512289.871     2225913.273      512440.965
     2225671.273      512402.4392225239.14310832512490.213560261
     2224768.718       512867.83     2224580.076      513173.821
2224036.97543713513510.4119478882223834.94215906513769.571877003
      2222550.76      514369.1652222186.51493534 514689.67509841
     2221975.644      514994.246     2221416.724      515124.471
      2221211.86      515250.105     2220779.828      515309.775
2220517.79922109515231.1194760322219786.06624405514786.048573896

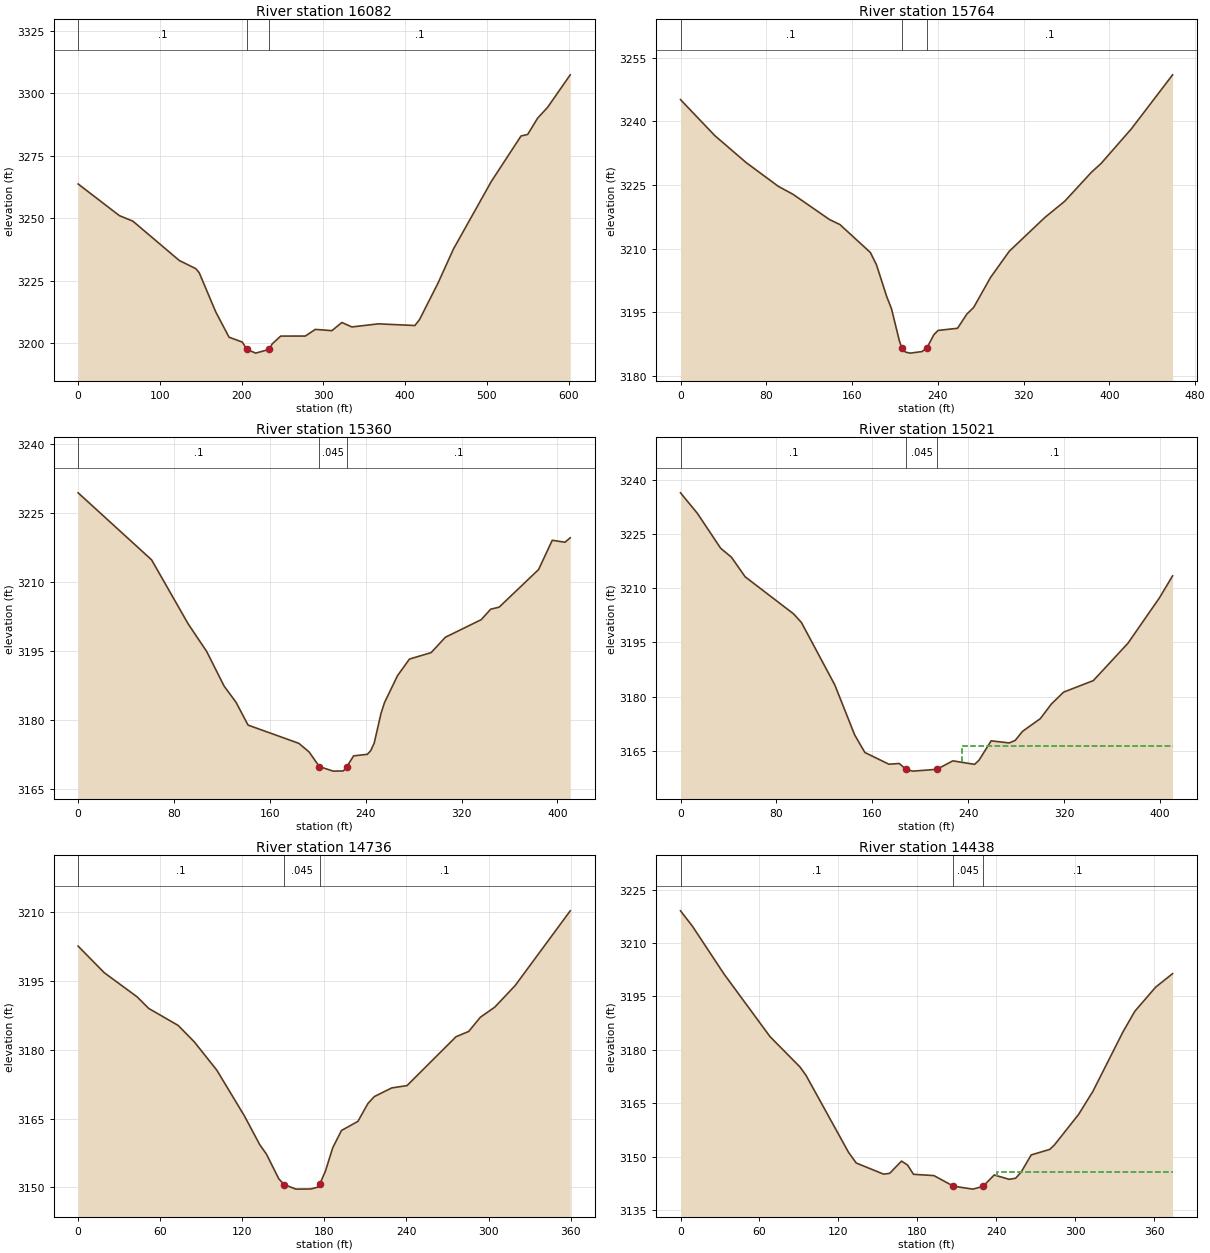
Type RM Length L Ch R = 1 ,16082   ,317.6,317.6,317.6
XS GIS Cut Line= 2
2232406.25722127507716.8544422422232999.44281696507818.782107979
#Sta/Elev= 30
       0 3263.66    50.6 3250.97    66.9  3248.8   123.7 3233.07     144 3229.78
   148.1 3228.16   168.3 3212.51   184.6 3202.38   200.8 3200.43   206.3 3197.54
   217.1 3196.01     234 3197.54   237.3 3199.69   247.8 3202.83   277.9 3202.84
   290.1  3205.5   310.4    3205   322.6 3208.27   334.8 3206.48   367.2 3207.72
   411.9 3207.05   417.6 3209.44   440.3  3224.1   459.1 3237.68   505.2 3264.57
   541.7 3282.85   549.9 3283.48     562 3289.98   574.2  3294.3   601.9 3307.31
#Mann= 3 ,-1,0
       0      .1       0   206.3    .045       0     234      .1       0
Bank Sta=206.3,234
XS Rating Curve= 0 ,0
Exp/Cntr(USF)=0,0
Exp/Cntr=0.3,0.1

Type RM Length L Ch R = 1 ,15764   ,407.8,404.8,400.8
XS GIS Cut Line= 4
2232359.47075176507838.8334520592232468.08219885507995.902314016
2232521.55244973508112.8684878132232621.80917013508209.783317531
#Sta/Elev= 30
       0 3245.15      32 3236.66    61.2  3230.3    91.3 3224.68     105  3222.8
     139 3216.85   148.7 3215.67   177.1 3209.08   182.8 3206.18   192.4 3198.64
   196.8 3195.82   204.1 3188.29  206.463186.504     210 3185.56   214.4 3185.33
   225.2  3185.7   229.7 3186.48   236.3 3189.67   240.3 3190.69   258.4 3191.19
   267.1 3194.54   273.5 3196.13   289.1 3203.15   306.7 3209.38   339.9 3217.35
   358.4 3221.17   383.3 3228.01   392.4 3230.11   420.7  3238.3     459    3251
#Mann= 3 ,-1,0
       0      .1       0  206.46    .045       0   229.7      .1       0
Bank Sta=206.46,229.7
XS Rating Curve= 0 ,0
Exp/Cntr(USF)=0,0
Exp/Cntr=0.3,0.1

Type RM Length L Ch R = 1 ,15360   ,339.1,339.1,338.9
XS GIS Cut Line= 2
 2232052.0168092508119.5522691732232297.64577418508448.728501146
#Sta/Elev= 30
       0 3229.31    61.3 3214.77    91.9 3200.85   107.3 3194.88   121.8 3187.39
   131.8 3183.86   141.8 3178.92   184.2 3174.96   192.8 3173.08   201.3 3169.92
   212.8 3168.93   221.4 3168.97   224.2 3169.87   229.9 3172.24   241.4 3172.58
   244.2 3173.38   247.1 3175.01   252.8 3181.48   255.7  3183.8   266.5 3189.62
   276.5 3193.24   294.6 3194.64   306.5 3197.98   336.4 3201.79   344.3 3204.06
   351.4 3204.51   384.3 3212.67   395.7 3219.02   406.3 3218.59   410.7 3219.55
#Mann= 3 ,-1,0
       0      .1       0   201.3    .045       0   224.2      .1       0
Bank Sta=201.3,224.2
XS Rating Curve= 0 ,0
Exp/Cntr(USF)=0,0
Exp/Cntr=0.3,0.1

Type RM Length L Ch R = 1 ,15021   ,287.9,284.4,282.1
XS GIS Cut Line= 2
2231791.34933617508338.4461087082232038.64924648508665.951395341
#Sta/Elev= 30
       0 3236.32      14 3230.69    33.5 3221.01    42.5 3218.53    53.9 3213.13
    94.3 3202.89   100.9 3200.48   128.7 3183.25   145.3 3169.42   153.8 3164.58
   173.8 3161.35   182.5 3161.55   188.2 3159.89   193.9 3159.44   213.9 3159.94
   213.9 3159.95   227.1 3162.28   245.3 3161.31     249 3162.48   259.1 3167.81
   274.1 3167.23   279.1 3167.92   285.3 3170.44   300.1 3173.94   309.2 3177.94
   319.5 3181.26   344.3 3184.45   373.1 3194.74   399.4 3207.29   410.4 3213.38
#Mann= 3 ,-1,0
       0      .1       0   188.2    .045       0   213.9      .1       0
#XS Ineff= 2 , 0
                          235.02         3166.47
Permanent Ineff=
       F       F
Bank Sta=188.2,213.9
XS Rating Curve= 0 ,0
Exp/Cntr(USF)=0,0
Exp/Cntr=0.3,0.1

Type RM Length L Ch R = 1 ,14736   ,291.2,298.5,302.9
XS GIS Cut Line= 2
2231585.82305935508572.3784563032231853.17431375508812.994585258
#Sta/Elev= 30
       0  3202.6    19.1 3196.81    43.1 3191.55    51.6 3189.02    73.1 3185.32
    84.9 3181.74   101.4 3175.55   121.6 3165.56   132.7 3159.35   137.7 3157.23
   146.7 3151.86   150.7 3150.61   159.2 3149.63     170 3149.66   175.4 3150.07
  176.583150.685   180.8  3153.6   186.1 3158.65   192.5 3162.42   204.5  3164.4
   211.8 3168.29   216.5 3169.81   229.2 3171.69   240.4  3172.2   276.2 3182.85
   285.5 3184.01     294  3187.1   304.5 3189.29   319.5 3194.03   359.7  3210.3
#Mann= 3 ,-1,0
       0      .1       0   150.7    .045       0  176.58      .1       0
Bank Sta=150.7,176.58
XS Rating Curve= 0 ,0
Exp/Cntr(USF)=0,0
Exp/Cntr=0.3,0.1

Type RM Length L Ch R = 1 ,14438   ,235.5,233.2,219.1
XS GIS Cut Line= 2
2231375.28394652508669.2932860212231552.40415255508998.469517994
#Sta/Elev= 30
       0 3219.02       9 3214.74    33.1 3201.27      68 3183.72    90.7 3175.23
    95.3 3172.88   127.6 3151.28   133.5 3148.25   154.3 3145.12   158.9 3145.36
   167.9 3148.79   172.5 3147.67     177 3145.08   192.5 3144.72   207.3 3141.75
   222.1 3140.92   229.8  3141.7   238.3 3144.89   249.7 3143.67   254.6 3143.98
   258.8 3145.73   266.4 3150.52   280.5 3152.07   284.1 3153.35   302.4 3161.89
   313.3 3168.38     336 3184.97   345.1 3190.82   360.9 3197.59   373.8 3201.39
#Mann= 3 ,-1,0
       0      .1       0   207.3    .045       0   229.8      .1       0
#XS Ineff= 2 , 0
                          240.46         3145.85
Permanent Ineff=
       F       F
Bank Sta=207.3,229.8
XS Rating Curve= 0 ,0
Exp/Cntr(USF)=0,0
Exp/Cntr=0.3,0.1

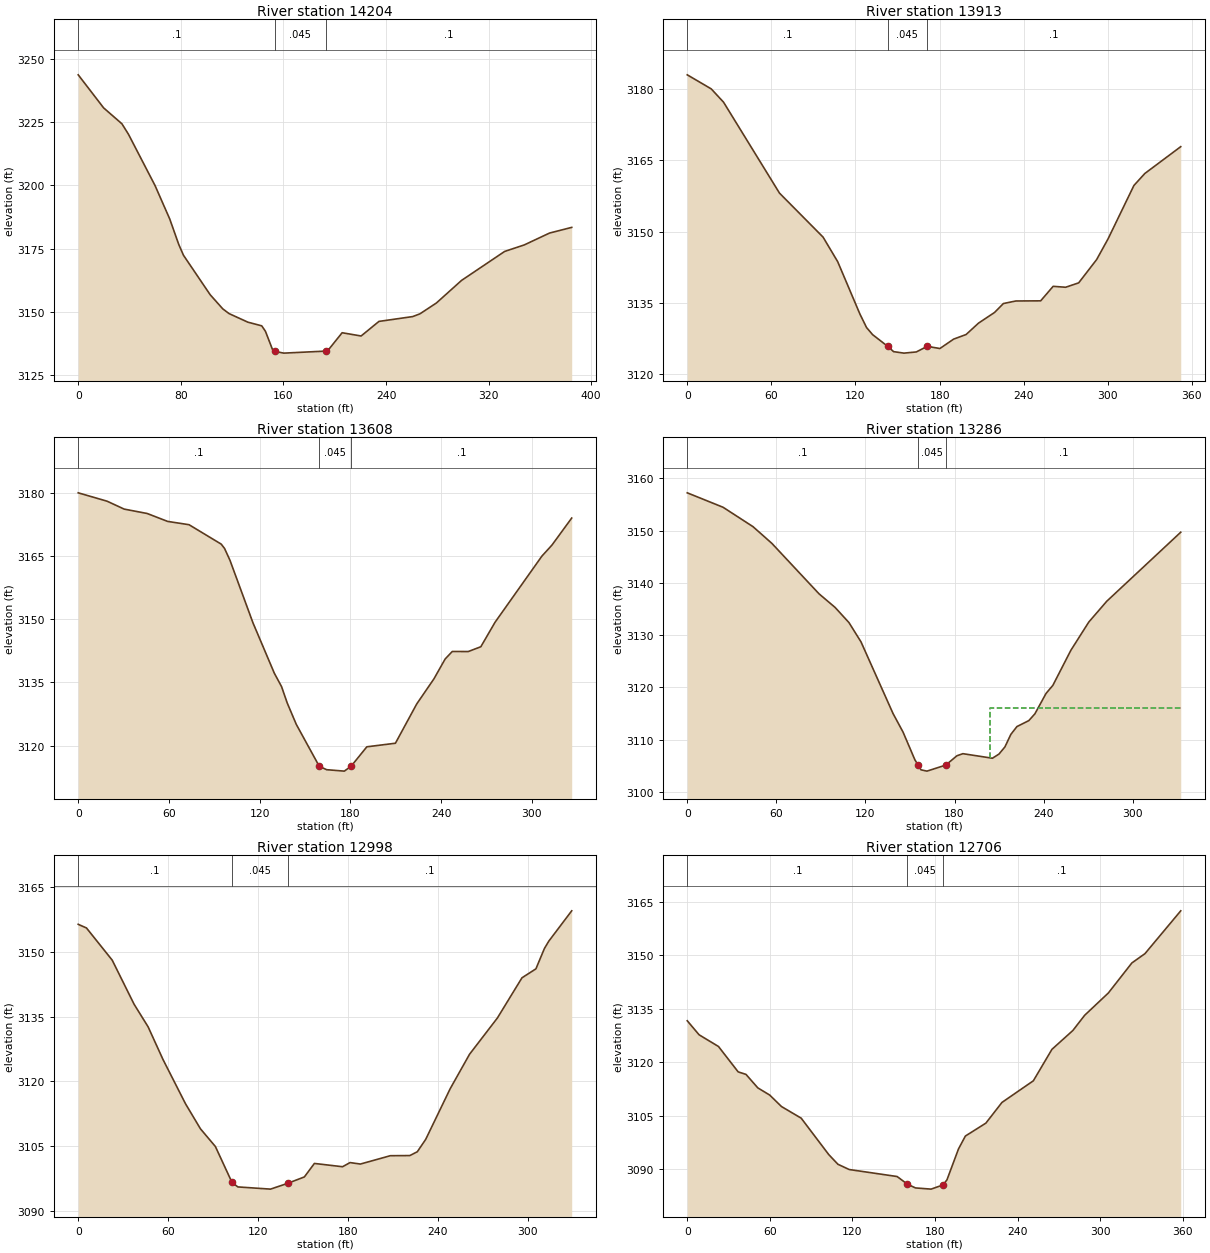
Type RM Length L Ch R = 1 ,14204   ,301.5,291.7,280.4
XS GIS Cut Line= 2
2231164.74483368508741.143935639 2231386.9805639509055.281659553
#Sta/Elev= 30
       0 3243.79    19.8 3230.72    34.1  3224.4    39.2 3220.26    59.9 3199.98
    71.4  3186.7    78.4 3176.66    82.1 3172.37   102.9 3156.77   112.7 3151.19
   117.6 3149.31   132.3 3145.91   143.1 3144.46     146  3142.3   151.7 3134.82
   153.3 3134.35   160.3 3133.66   192.9 3134.46     196 3135.54   205.8 3141.73
   220.6 3140.44   234.5 3146.21   260.8 3148.12   266.5 3149.22   279.3  3153.5
   298.9 3162.43   332.5  3173.9   347.9  3176.5   367.5 3181.17   384.8 3183.42
#Mann= 3 ,-1,0
       0      .1       0   153.3    .045       0   192.9      .1       0
Bank Sta=153.3,192.9
XS Rating Curve= 0 ,0
Exp/Cntr(USF)=0,0
Exp/Cntr=0.3,0.1

Type RM Length L Ch R = 1 ,13913   ,293.5,304.3,312.8
XS GIS Cut Line= 2
2230920.78681405509020.1918074132231238.26642864 509172.24783335
#Sta/Elev= 30
       0 3183.03    17.1 3180.07    25.9 3177.26    65.8  3158.1    96.9 3148.82
   107.3 3143.66   123.2 3132.59   127.9 3129.77   132.2 3128.28  142.89 3125.83
   147.2 3124.69   154.6 3124.38   163.4 3124.63   171.2 3125.81   180.2 3125.35
     190 3127.33   198.9  3128.3   207.8 3130.71   219.2 3132.95   225.5 3134.83
   234.4 3135.37   252.1  3135.4     261 3138.46   269.9 3138.26   279.2 3139.19
     292 3144.09   300.2 3148.48   318.6 3159.71   326.4 3162.24     352 3167.89
#Mann= 3 ,-1,0
       0      .1       0  142.89    .045       0   171.2      .1       0
Bank Sta=142.89,171.2
XS Rating Curve= 0 ,0
Exp/Cntr(USF)=0,0
Exp/Cntr=0.3,0.1

Type RM Length L Ch R = 1 ,13608   ,315.7,322.6,327.8
XS GIS Cut Line= 2
2230792.12402287 509178.931614712230964.23139289509456.308541144
#Sta/Elev= 30
       0 3180.08    19.1 3178.09    30.4 3176.21    45.6 3175.17    59.1 3173.29
    73.3  3172.5    94.6 3167.88    96.8 3166.85   100.4 3164.02   115.6 3149.16
   129.7 3137.21   134.5 3134.01   138.2 3130.16   144.2 3125.06   159.4 3115.09
   164.3 3114.26     176 3113.92   180.5 3115.08   190.9  3119.7   209.8 3120.55
   223.9 3129.89   235.3 3135.87   242.7 3140.58   247.4 3142.36     258 3142.35
   266.3 3143.49   275.7 3149.31   306.7 3165.04   313.3 3167.64   326.4 3174.08
#Mann= 3 ,-1,0
       0      .1       0   159.4    .045       0   180.5      .1       0
Bank Sta=159.4,180.5
XS Rating Curve= 0 ,0
Exp/Cntr(USF)=0,0
Exp/Cntr=0.3,0.1

Type RM Length L Ch R = 1 ,13286   ,305.2,287.3,275.2
XS GIS Cut Line= 2
2230579.91396469509309.2653512272230625.02948887  509638.4415832
#Sta/Elev= 30
       0 3157.24    24.1 3154.48    44.3 3150.76      57 3147.56    88.7 3137.92
    99.6 3135.29   108.9  3132.4     117 3128.71   138.6 3114.98   145.3 3111.45
   153.3 3106.13  155.473105.119   157.4 3104.22   161.4 3103.97   174.1 3105.13
   181.6 3106.91   185.6 3107.31   205.5 3106.44   209.9 3107.23   213.9  3108.6
   217.9    3111     222  3112.5     230 3113.64   234.1 3114.94   241.6 3118.84
   246.2 3120.39   258.3 3127.09   270.4 3132.51   282.5 3136.49   332.3  3149.7
#Mann= 3 ,-1,0
       0      .1       0  155.47    .045       0   174.1      .1       0
#XS Ineff= 2 , 0
                          203.76          3116.1
Permanent Ineff=
       F       F
Bank Sta=155.47,174.1
XS Rating Curve= 0 ,0
Exp/Cntr(USF)=0,0
Exp/Cntr=0.3,0.1

Type RM Length L Ch R = 1 ,12998   ,291.4,292.5,291.8
XS GIS Cut Line= 2
 2230270.7890768509534.8429721222230534.79844052509732.014522238
#Sta/Elev= 30
       0 3156.33     5.5 3155.49    22.7 3148.04    37.3 3137.85    46.7  3132.6
    56.6 3125.07    71.6 3114.85    81.6 3109.04    91.6 3104.93   102.7 3096.62
   106.6 3095.59   128.4 3095.08   139.8 3096.41     151  3097.9   157.7 3101.02
   176.5 3100.26   181.5 3101.22   188.4 3100.88   208.4 3102.81   221.4 3102.84
   226.4 3103.72     232 3106.58   248.4 3118.33   261.3 3126.28   279.9 3134.67
   296.3 3143.96   305.6 3146.03   311.3 3150.75   314.2 3152.43   329.5 3159.45
#Mann= 3 ,-1,0
       0      .1       0   102.7    .045       0   139.8      .1       0
Bank Sta=102.7,139.8
XS Rating Curve= 0 ,0
Exp/Cntr(USF)=0,0
Exp/Cntr=0.3,0.1

Type RM Length L Ch R = 1 ,12706   ,285.3,288.8,291.2
XS GIS Cut Line= 2
2230065.26279999509740.369248938 2230354.3363438509952.579307113
#Sta/Elev= 30
       0  3131.6     8.6 3127.67    22.7 3124.39      37 3117.28    42.7 3116.57
    51.3 3112.79    59.9 3110.79    68.5 3107.56    82.8 3104.31   102.8 3094.12
   109.5 3091.39   117.7 3089.92   152.5 3087.96     160 3085.81   165.8 3084.77
   177.2 3084.43   185.8  3085.6   188.7 3087.01   197.1 3095.68   202.1  3099.3
     217 3102.92   228.7 3108.72   251.5 3114.78     265 3123.59   280.2 3128.87
   288.8 3133.14     306 3139.38   323.1  3147.8   332.6  3150.4   358.6  3162.4
#Mann= 3 ,-1,0
       0      .1       0     160    .045       0   185.8      .1       0
Bank Sta=160,185.8
XS Rating Curve= 0 ,0
Exp/Cntr(USF)=0,0
Exp/Cntr=0.3,0.1

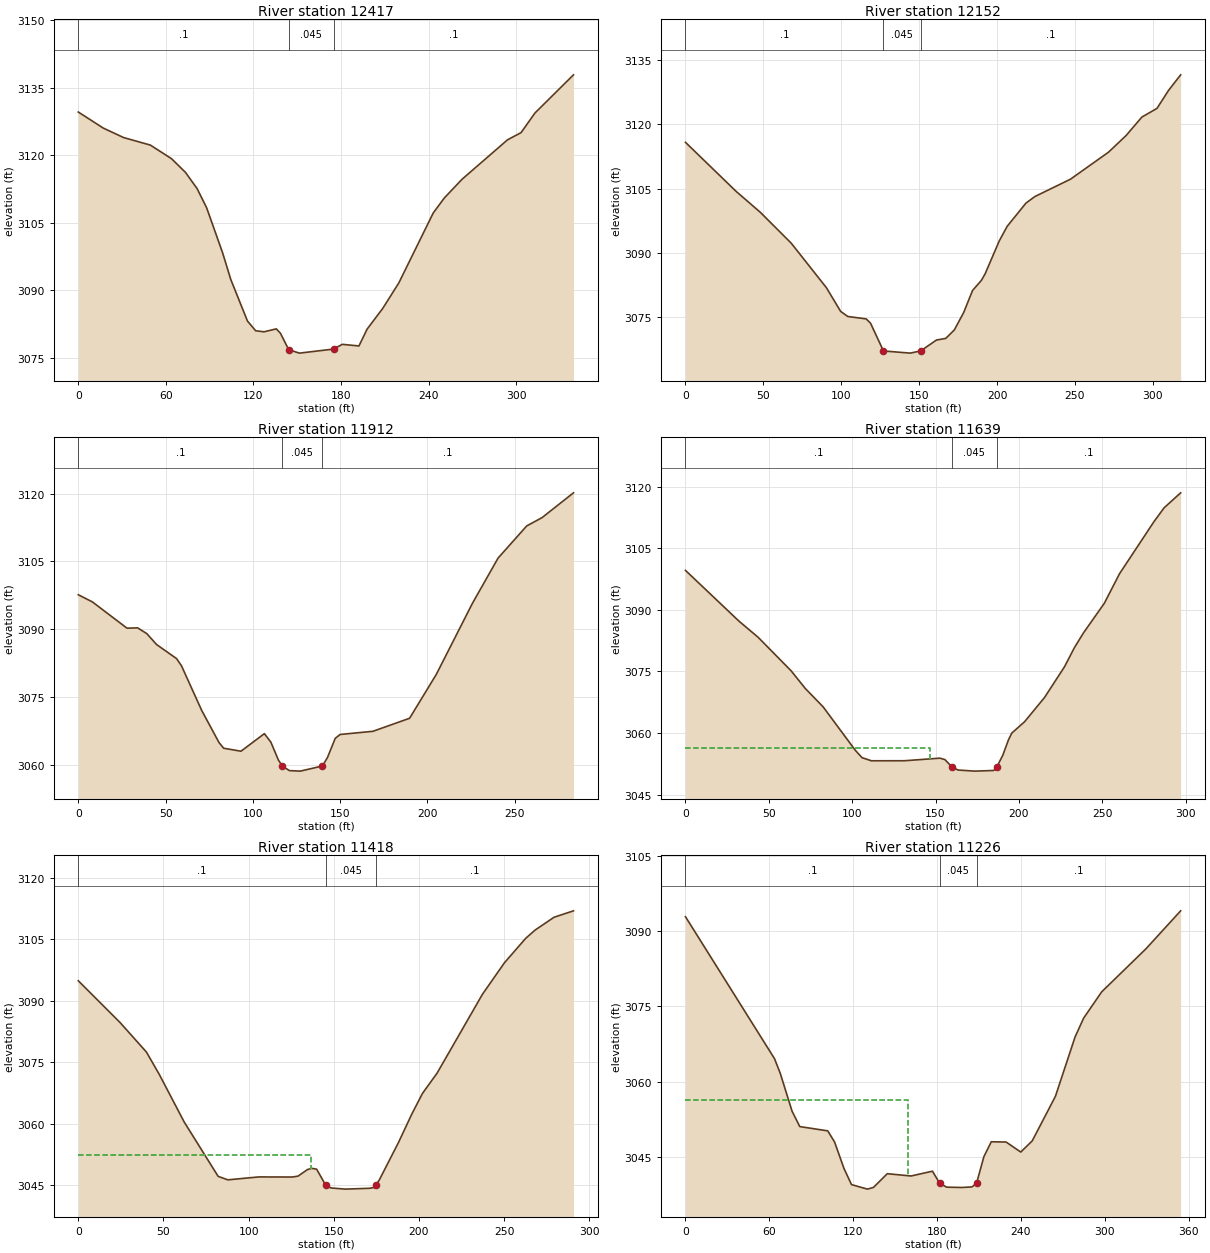
Type RM Length L Ch R = 1 ,12417   ,265.8,265.1,264.4
XS GIS Cut Line= 2
2229876.44597657509909.1347282742230108.70737883510156.434638589
#Sta/Elev= 30
       0 3129.58    17.1 3126.02      31 3123.92    49.4 3122.24    63.9 3119.22
    73.4  3116.2    81.4  3112.6    87.9 3108.37    98.9 3098.33   104.5 3092.41
   115.9 3083.22   121.5 3081.06   127.2 3080.82   135.7 3081.47   138.5  3080.5
   144.2 3076.84   151.5 3076.09   174.9 3076.99   180.9 3078.04   192.3 3077.68
   197.9 3081.42   208.6 3086.01   219.6 3091.65   243.2 3107.18   250.8 3110.51
     263 3114.68   294.1 3123.41   303.4 3125.01   312.9 3129.36   339.3 3137.83
#Mann= 3 ,-1,0
       0      .1       0   144.2    .045       0   174.9      .1       0
Bank Sta=144.2,174.9
XS Rating Curve= 0 ,0
Exp/Cntr(USF)=0,0
Exp/Cntr=0.3,0.1

Type RM Length L Ch R = 1 ,12152   ,241.4,239.9,238.5
XS GIS Cut Line= 2
2229700.99671587510116.3319504292229928.24528211510338.567680645
#Sta/Elev= 30
       0 3115.82    32.4 3104.41    48.1 3099.47    67.9 3092.28    90.5 3081.88
    99.6 3076.37   104.2 3075.17     116 3074.61   118.8 3073.61   127.1 3067.13
   144.3 3066.62  151.063067.147   161.1 3069.67   167.1 3070.06   172.6 3072.03
   178.6 3076.09   184.3 3081.24     190 3083.61   192.4 3085.15   201.4 3092.77
   206.5  3096.2   218.6 3101.64   224.3 3103.16   247.2 3107.22   271.6 3113.52
   282.9 3117.41     293 3121.71   302.7 3123.74   310.1 3127.92   317.9 3131.57
#Mann= 3 ,-1,0
       0      .1       0   127.1    .045       0  151.06      .1       0
Bank Sta=127.1,151.06
XS Rating Curve= 0 ,0
Exp/Cntr(USF)=0,0
Exp/Cntr=0.3,0.1

Type RM Length L Ch R = 1 ,11912   ,272.3,273.4,274.3
XS GIS Cut Line= 2
2229553.95352596510320.1872819052229772.84736549510500.649378621
#Sta/Elev= 30
       0 3097.64     8.1 3096.05    27.9 3090.25      34 3090.32    39.2 3089.06
    44.9 3086.62    56.3 3083.53    59.1 3081.95    70.7 3072.08    80.6 3064.99
    83.3 3063.72    93.2 3063.06   106.6 3066.94   110.3 3065.08   114.7 3061.07
   116.9 3059.76     121 3058.77   127.2 3058.66   139.9  3059.8   142.8 3061.71
   147.2  3065.9     150 3066.76   168.8 3067.46   189.8 3070.34   205.1 3080.03
   225.8 3095.74   240.5 3105.74   256.9 3112.84   265.7 3114.68   283.7 3120.16
#Mann= 3 ,-1,0
       0      .1       0   116.9    .045       0   139.9      .1       0
Bank Sta=116.9,139.9
XS Rating Curve= 0 ,0
Exp/Cntr(USF)=0,0
Exp/Cntr=0.3,0.1

Type RM Length L Ch R = 1 ,11639   ,219.9,220.6,221.2
XS GIS Cut Line= 2
2229366.80764788510509.0041053212229587.37243276510707.846600777
#Sta/Elev= 30
       0 3099.63    32.2 3087.22    43.6 3083.32    63.4 3075.14    71.9 3070.84
    82.6 3066.36   101.8 3055.82   105.9 3053.99   111.5 3053.23   131.4 3053.24
   152.6 3053.87   155.6 3053.52   159.7 3051.79   163.4 3050.98   173.5 3050.71
   184.9 3050.87  186.873051.821   190.3 3054.56   193.7  3058.3   195.7 3059.97
   203.4 3062.75   215.3 3068.62   227.3 3076.12   233.3 3080.82   238.8 3084.45
   251.2  3091.6   260.3 3098.79     281 3111.51   287.1 3114.89     297 3118.53
#Mann= 3 ,-1,0
       0      .1       0   159.7    .045       0  186.87      .1       0
#XS Ineff= 2 , 0
          146.37 3056.34
Permanent Ineff=
       F       F
Bank Sta=159.7,186.87
XS Rating Curve= 0 ,0
Exp/Cntr(USF)=0,0
Exp/Cntr=0.3,0.1

Type RM Length L Ch R = 1 ,11418   ,193.6,192.5,191.6
XS GIS Cut Line= 2
2229231.46107535510676.0986393172229440.32924284510878.283025453
#Sta/Elev= 30
       0 3094.88    24.6 3084.64      40 3077.46    47.6 3071.96    62.2 3060.35
    82.1 3047.09    87.8 3046.24   105.9 3046.95   125.7 3046.93     129 3047.15
   134.6 3048.76   137.1 3049.04   139.9 3048.85   145.3  3044.9   148.4 3044.25
   156.9 3043.97     171 3044.18   173.6 3044.36  174.693044.919   176.7 3046.21
     188 3055.39   195.8 3062.32   202.1 3067.39   210.6 3072.29   237.3 3091.61
   250.2 3099.29   262.6 3105.23   268.2 3107.28   279.3  3110.4   290.7 3111.97
#Mann= 3 ,-1,0
       0      .1       0   145.3    .045       0  174.69      .1       0
#XS Ineff= 2 , 0
          136.73 3052.31
Permanent Ineff=
       F       F
Bank Sta=145.3,174.69
XS Rating Curve= 0 ,0
Exp/Cntr(USF)=0,0
Exp/Cntr=0.3,0.1

Type RM Length L Ch R = 1 ,11226   ,231.2,230.4,231.4
XS GIS Cut Line= 2
2229066.03748669510799.7485944752229335.05968642 511030.33905139
#Sta/Elev= 30
       0 3092.92    63.7 3064.59    67.8 3061.68    76.3 3054.08    81.8 3051.03
   101.8 3050.18   106.7 3047.95   113.4 3042.68   118.8 3039.45   130.2 3038.55
   134.5 3038.89   144.4 3041.63   161.4 3041.17   176.7 3042.13   181.9 3039.72
   186.9 3038.94   197.7 3038.88     205 3038.99   208.3 3039.75   213.5 3045.02
   218.8    3048   229.4 3047.95   239.9 3045.95   248.1 3048.18   264.7 3057.07
   278.8 3068.95   284.9 3072.68   297.8 3077.92   329.5 3086.52   354.3 3094.09
#Mann= 3 ,-1,0
       0      .1       0   181.9    .045       0   208.3      .1       0
#XS Ineff= 2 , 0
          159.14 3056.25
Permanent Ineff=
       F       F
Bank Sta=181.9,208.3
XS Rating Curve= 0 ,0
Exp/Cntr(USF)=0,0
Exp/Cntr=0.3,0.1

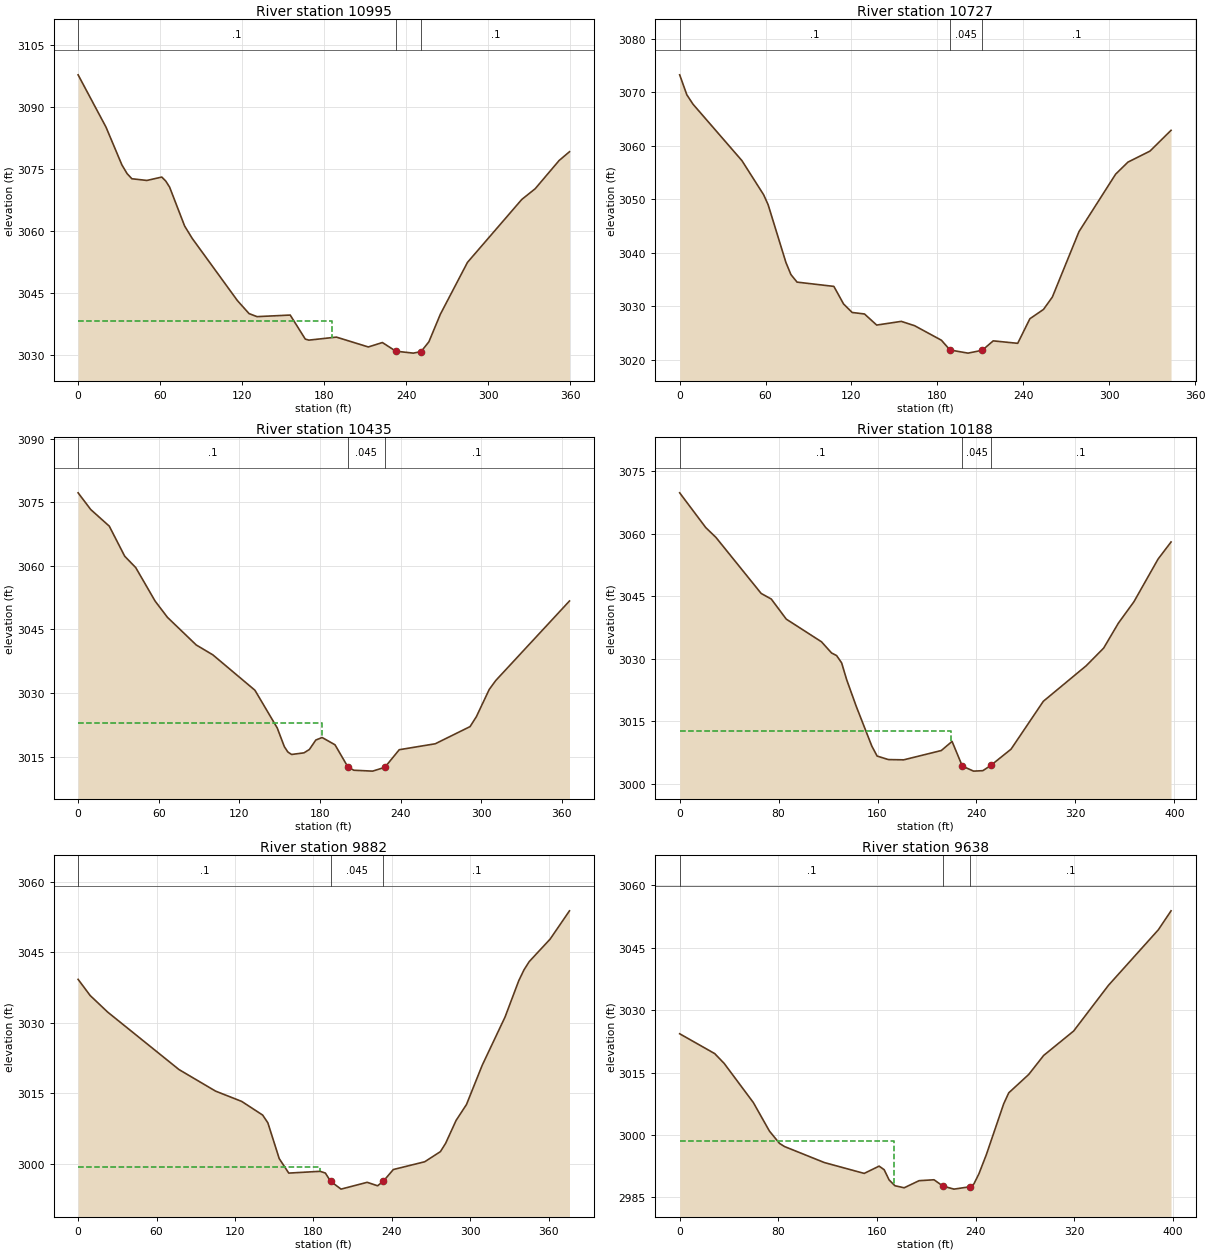
Type RM Length L Ch R = 1 ,10995   ,259.9,268.2,274.1
XS GIS Cut Line= 2
2228915.65240609510955.1465110912229176.31987913511202.446421406
#Sta/Elev= 30
       0  3097.7    20.4 3085.06      32 3075.94    35.8 3073.83    39.3 3072.58
    50.3 3072.17    61.2 3072.99    64.1 3072.02    66.9 3070.56    77.9 3061.15
    83.4 3058.18   116.5 3043.12     125 3039.99   130.8 3039.25   155.1 3039.63
   166.1 3033.83   168.7 3033.57   188.9  3034.3   212.2 3031.92   222.5 3032.99
   232.3  3030.9   245.1 3030.43   250.8  3030.8   256.5 3033.17   264.9 3039.84
   284.7 3052.36   324.4 3067.57   334.2 3070.16   351.7 3076.98   359.3 3079.11
#Mann= 3 ,-1,0
       0      .1       0   232.3    .045       0   250.8      .1       0
#XS Ineff= 2 , 0
          185.92  3038.1
Permanent Ineff=
       F       F
Bank Sta=232.3,250.8
XS Rating Curve= 0 ,0
Exp/Cntr(USF)=0,0
Exp/Cntr=0.3,0.1

Type RM Length L Ch R = 1 ,10727   ,296.4,292.2,289.4
XS GIS Cut Line= 2
2228817.06663104511100.5187556682228939.04564085511421.340260941
#Sta/Elev= 30
       0 3073.25       5 3069.52     9.3 3067.77    43.5 3057.22    58.7 3050.83
    61.8 3048.98    74.2 3038.22    77.7 3035.95      82 3034.54   107.7 3033.74
   114.5 3030.45   120.5 3028.87   129.1 3028.59   137.6 3026.52   154.8 3027.21
   164.1  3026.4   182.8 3023.69   188.8 3021.87   201.4 3021.28   211.3 3021.81
     219 3023.57   236.1 3023.11   244.6  3027.7   254.1 3029.44   260.3 3031.75
   278.9 3043.97   304.5  3054.7   313.1 3056.95   328.5 3059.01   343.2 3062.89
#Mann= 3 ,-1,0
       0      .1       0   188.8    .045       0   211.3      .1       0
Bank Sta=188.8,211.3
XS Rating Curve= 0 ,0
Exp/Cntr(USF)=0,0
Exp/Cntr=0.3,0.1

Type RM Length L Ch R = 1 ,10435   ,243.3,246.4,249.5
XS GIS Cut Line= 2
2228527.99308722511269.2842350042228728.50652802511575.067232218
#Sta/Elev= 30
       0 3077.21     9.4 3073.27    23.2 3069.35    34.7 3062.25    42.9 3059.57
    57.3 3051.68    66.5 3047.84    87.9 3041.33   100.3 3038.99   131.6 3030.65
   148.2 3021.75   153.5 3017.34   156.1 3016.08   158.9  3015.5   168.1 3015.88
   172.1 3016.67   176.9  3018.9   181.6  3019.5   191.2 3017.78   200.8 3012.55
   205.2 3011.78   219.2 3011.57   228.3 3012.47     239 3016.62   265.8 3018.02
   291.7 3022.07   296.4 3024.41     306 3030.85   310.8 3032.93   365.7  3051.7
#Mann= 3 ,-1,0
       0      .1       0   200.8    .045       0   228.3      .1       0
#XS Ineff= 2 , 0
          181.86 3022.99
Permanent Ineff=
       F       F
Bank Sta=200.8,228.3
XS Rating Curve= 0 ,0
Exp/Cntr(USF)=0,0
Exp/Cntr=0.3,0.1

Type RM Length L Ch R = 1 ,10188   ,297.5,306.1,314.3
XS GIS Cut Line= 3
2228374.63103668511344.400240663 2228403.3928834511499.672532493
2228496.24512576511720.439476795
#Sta/Elev= 30
       0 3069.78    21.1 3061.44    29.3  3059.1    65.9 3045.65    74.1  3044.3
    86.2 3039.49   114.7 3034.05   122.8 3031.38   126.9 3030.75     131 3028.99
     135 3025.01   142.7 3018.65   155.4 3009.03   159.7 3006.64   168.8  3005.8
   181.2 3005.74   211.6 3007.97   220.3 3010.16228.58633004.232   237.7 3003.03
   245.2 3003.14 251.5863004.387     268  3008.3   294.1 3019.78   328.8 3028.31
   342.9 3032.54   354.8 3038.52   367.4 3043.67   386.9 3053.89   397.4 3057.99
#Mann= 3 ,-1,0
       0      .1       0228.5863    .045       0 251.586      .1       0
#XS Ineff= 2 , 0
          219.04 3012.61
Permanent Ineff=
       F       F
Bank Sta=228.5863,251.586
XS Rating Curve= 0 ,0
Exp/Cntr(USF)=0,0
Exp/Cntr=0.3,0.1

Type RM Length L Ch R = 1 ,9882    ,247.6,244.6,241.3
XS GIS Cut Line= 2
2228145.34660437511428.0240423012228150.35944039511803.986743793
#Sta/Elev= 30
       0 3039.22     9.2 3035.79    22.6 3032.26    77.2 3020.03   105.2 3015.44
   125.2 3013.25   141.2 3010.35   145.2  3008.7   153.9 3001.08   161.2    2998
   185.2 2998.38   189.2 2998.01   193.2 2996.26   201.2 2994.59   221.2 2996.04
   229.2  2995.3   233.5 2996.26   241.2 2998.76   265.2 3000.41   277.2 3002.56
   281.2 3004.32   289.2 3009.19   297.2  3012.6   309.2 3020.93   326.7 3031.21
   337.2 3038.94   341.2 3041.25   345.2    3043   361.2 3047.79     376  3053.8
#Mann= 3 ,-1,0
       0      .1       0   193.2    .045       0   233.5      .1       0
#XS Ineff= 2 , 0
          184.94  2999.2
Permanent Ineff=
       F       F
Bank Sta=193.2,233.5
XS Rating Curve= 0 ,0
Exp/Cntr(USF)=0,0
Exp/Cntr=0.3,0.1

Type RM Length L Ch R = 1 ,9638    ,261.3,256.8,252.1
XS GIS Cut Line= 2
 2227874.6534593  511453.08822242227931.46560086511847.431322632
#Sta/Elev= 30
       0 3024.32    28.4 3019.55    36.1 3017.18    59.7 3007.79    72.8 3000.91
    80.9 2997.97      85  2997.2   117.3 2993.35   149.6 2990.74   161.7 2992.49
   165.8 2991.63   169.8 2989.18   174.5 2987.78     182 2987.28   194.1 2988.99
   206.2 2989.21   213.4  2987.7   222.4 2986.96   235.1 2987.52   238.5 2988.19
   242.6 2990.63   248.6 2995.21   262.7 3007.47   266.8 3010.11     283 3014.53
   295.1  3019.1   319.4 3024.97   347.6 3035.95   388.1 3049.32   398.4 3053.88
#Mann= 3 ,-1,0
       0      .1       0   213.4    .045       0   235.1      .1       0
#XS Ineff= 2 , 0
          173.89 2998.53
Permanent Ineff=
       F       F
Bank Sta=213.4,235.1
XS Rating Curve= 0 ,0
Exp/Cntr(USF)=0,0
Exp/Cntr=0.3,0.1

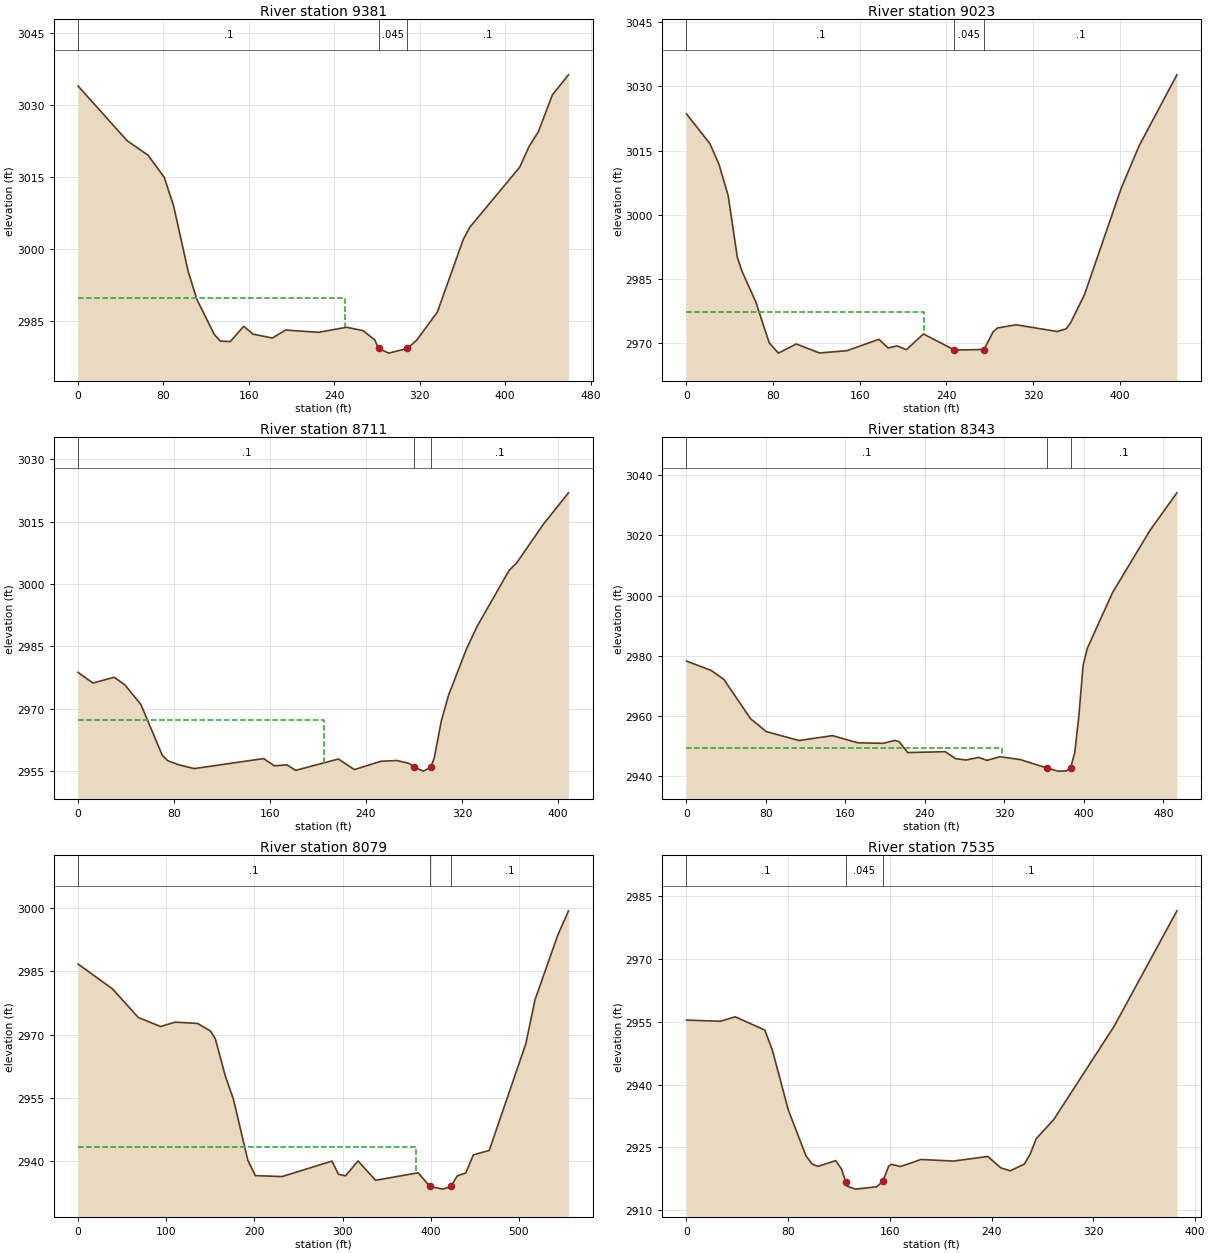
Type RM Length L Ch R = 1 ,9381    ,355.9,358.2,359.2
XS GIS Cut Line= 2
2227545.47722732 511491.51996522 2227732.6231054511910.927245551
#Sta/Elev= 30
       0 3034.01    45.9 3022.59    65.5 3019.57    80.7 3014.92    89.4 3009.05
   103.2 2995.24   111.3 2989.42   127.5 2982.16   133.2 2980.73   142.6 2980.63
   155.1 2983.82   163.9 2982.19     182 2981.38   194.5 2983.04   225.2 2982.57
   251.5 2983.62   266.9 2982.92   277.8 2980.99   281.5 2979.19   290.9 2978.22
   308.4 2979.19   317.2 2980.94   336.5  2986.8   360.7 3001.93   366.7 3004.47
   413.6 3017.05   422.3 3021.33   431.1 3024.47   444.2 3032.15   459.3 3036.34
#Mann= 3 ,-1,0
       0      .1       0   281.5    .045       0   308.4      .1       0
#XS Ineff= 2 , 0
          250.42 2989.72
Permanent Ineff=
       F       F
Bank Sta=281.5,308.4
XS Rating Curve= 0 ,0
Exp/Cntr(USF)=0,0
Exp/Cntr=0.3,0.1

Type RM Length L Ch R = 1 ,9023    ,315.1,311.7,308.6
XS GIS Cut Line= 2
2227239.69423011511556.6868334782227383.39552935511986.119785849
#Sta/Elev= 30
       0 3023.55    21.6 3016.62      30  3011.8    38.5 3004.49    46.9 2990.15
    51.1 2986.93      64 2979.67    76.4 2970.12    84.9 2967.72   101.4 2969.86
   122.8 2967.76   148.1 2968.29   177.7 2970.95   186.1 2968.92   194.5 2969.41
     203 2968.52   218.8 2972.19   247.3 2968.46   247.3 2968.45   274.7 2968.56
   283.1 2972.69   287.3  2973.6   304.3 2974.34   342.3 2972.76   350.6 2973.41
   354.5 2974.74   367.4 2981.32   401.2 3006.09   417.9  3016.1   452.8 3032.67
#Mann= 3 ,-1,0
       0      .1       0   247.3    .045       0   274.7      .1       0
#XS Ineff= 2 , 0
          219.44 2977.21
Permanent Ineff=
       F       F
Bank Sta=247.3,274.7
XS Rating Curve= 0 ,0
Exp/Cntr(USF)=0,0
Exp/Cntr=0.3,0.1

Type RM Length L Ch R = 1 ,8711    ,366.5,368.4,369.3
XS GIS Cut Line= 2
2226930.56934222511702.0590780552227109.36049359512069.667052847
#Sta/Elev= 30
       0 2978.75    12.4  2976.2    30.2 2977.58    39.1 2975.74    52.4 2971.03
    70.2 2958.81    74.6 2957.53    83.5 2956.56    96.9 2955.61   154.7 2958.02
   163.6 2956.28   174.1 2956.51   181.4 2955.19     217 2957.91   230.3 2955.37
   252.6 2957.38   265.9 2957.55   275.9 2956.86   280.4 2955.92   287.8    2955
   293.8 2955.89   296.8 2958.03   302.8 2967.08   308.8 2973.24   323.7 2984.35
   332.6 2989.82   359.3  3003.3   365.6 3005.09   387.8 3014.37   408.8 3021.96
#Mann= 3 ,-1,0
       0      .1       0   280.4    .045       0   293.8      .1       0
#XS Ineff= 2 , 0
          205.07 2967.35
Permanent Ineff=
       F       F
Bank Sta=280.4,293.8
XS Rating Curve= 0 ,0
Exp/Cntr(USF)=0,0
Exp/Cntr=0.3,0.1

Type RM Length L Ch R = 1 ,8343    ,267.8,263.7,254.8
XS GIS Cut Line= 2
2226634.81201704511725.4523128152226786.86804298512194.987953344
#Sta/Elev= 30
       0 2978.23    24.9 2975.09    37.6 2972.13    64.4  2959.1    80.3 2954.78
   113.2 2951.81   146.9 2953.44   172.4 2951.06   197.8 2950.88   209.9 2951.84
   214.1 2951.37   222.6 2947.81   260.4  2948.1   270.8 2945.79   281.4 2945.33
     294 2946.21   302.4 2945.21   315.3 2946.43   336.1 2945.46   362.9 2942.66
   373.9 2941.64   382.3 2941.69   386.5 2942.76   390.7 2947.78   394.7  2959.5
   399.1 2976.79   403.3 2982.41   428.6 3000.89   466.4 3021.64   493.5 3034.13
#Mann= 3 ,-1,0
       0      .1       0   362.9    .045       0   386.5      .1       0
#XS Ineff= 2 , 0
          317.46 2949.39
Permanent Ineff=
       F       F
Bank Sta=362.9,386.5
XS Rating Curve= 0 ,0
Exp/Cntr(USF)=0,0
Exp/Cntr=0.3,0.1

Type RM Length L Ch R = 1 ,8079    ,543.1,544.3,546.9
XS GIS Cut Line= 3
2226307.30673041511824.0380878722226349.08036391 511956.04276973
2226614.76067296512278.535220343
#Sta/Elev= 30
       0 2986.75      39 2980.86    68.3 2974.08    93.5 2971.93   110.3 2972.97
   135.5 2972.66   150.3 2970.86   155.7 2969.04     167 2960.21   176.2 2954.72
   192.6 2940.21   201.1 2936.58   231.4 2936.36     288 2940.02   295.4 2936.91
   303.4 2936.54   317.6 2940.06   337.5 2935.47   385.8 2937.26   399.1 2934.01
   413.8 2933.38   422.8 2934.01   430.2 2936.53   439.8 2937.19   448.4 2941.49
   466.4 2942.56   507.9 2967.83   518.3 2978.25   544.2 2993.63   556.3 2999.36
#Mann= 3 ,-1,0
       0      .1       0   399.1    .045       0   422.8      .1       0
#XS Ineff= 2 , 0
          382.99  2943.3
Permanent Ineff=
       F       F
Bank Sta=399.1,422.8
XS Rating Curve= 0 ,0
Exp/Cntr(USF)=0,0
Exp/Cntr=0.3,0.1

Type RM Length L Ch R = 1 ,7535    ,219.3,229.6,255.5
XS GIS Cut Line= 2
2225964.76293572512240.1034775232226160.26354049512572.621600176
#Sta/Elev= 30
       0  2955.4    26.7 2955.12    38.3 2956.19    61.6 2953.02    67.6 2948.17
    80.1  2933.9    93.9 2923.01    98.7 2921.03   103.3 2920.43   117.3 2921.81
   121.9 2919.84   125.1 2916.81   126.5 2915.68     133    2915   149.7 2915.57
   154.4 2916.88     159 2920.46   161.1 2920.93   168.3  2920.4   184.4 2922.08
   210.1 2921.71     237  2922.8   247.2 2920.09   254.6 2919.38   265.7 2920.99
   270.4 2923.43     275 2927.03   288.9 2931.65   336.4 2953.96   385.7 2981.52
#Mann= 3 ,-1,0
       0      .1       0   125.1    .045       0   154.4      .1       0
Bank Sta=125.1,154.4
XS Rating Curve= 0 ,0
Exp/Cntr(USF)=0,0
Exp/Cntr=0.3,0.1