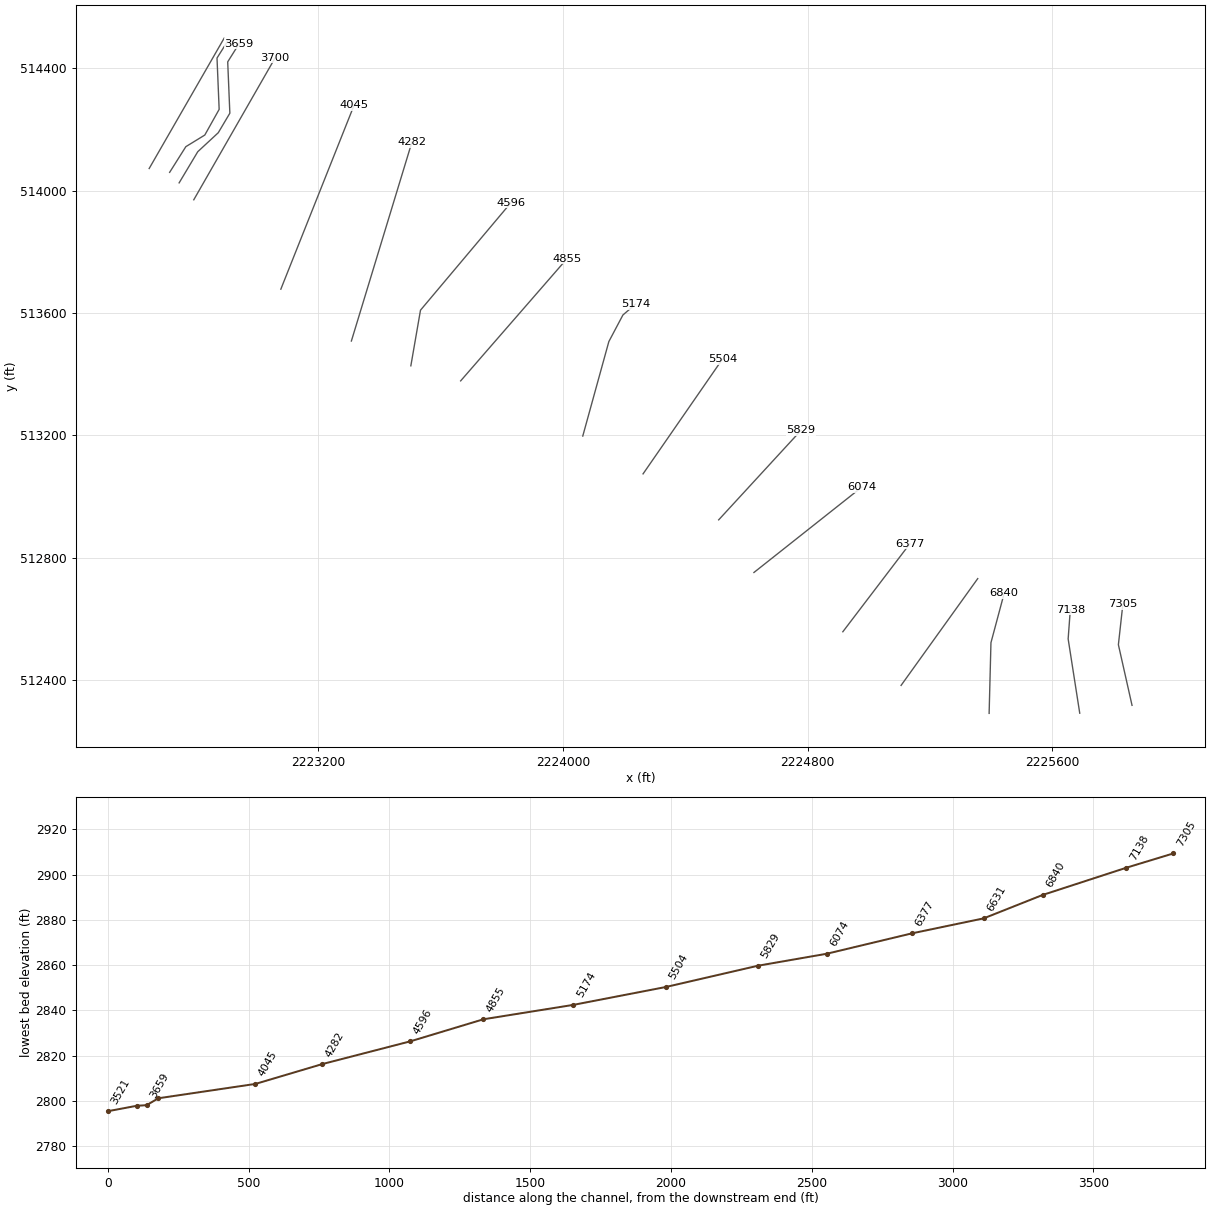
HEC-RAS study SLTYFK.prj: SLTYFK

--- SLTYFK.g01 (geometry) --- (continued)

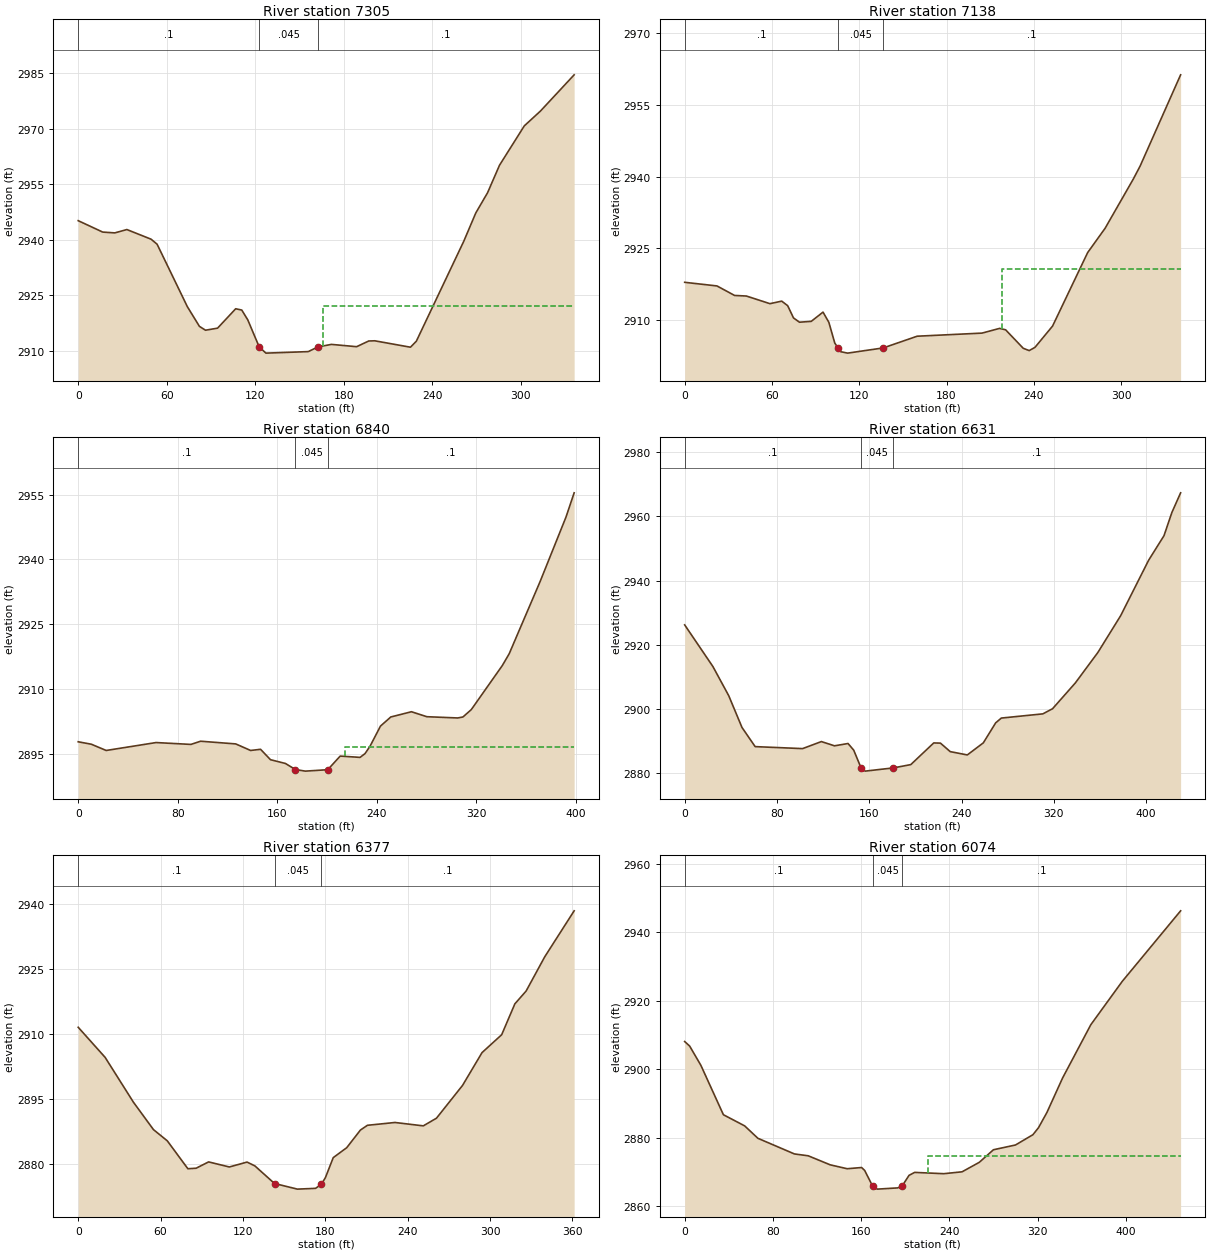
Type RM Length L Ch R = 1 ,7305    ,169.3,167.1,165.6
XS GIS Cut Line= 3
2225861.16432464512316.9669631622225816.55415152512515.233427377
2225831.17678021512647.547519346
#Sta/Elev= 30
       0 2945.17    16.6 2942.09    24.8 2941.87      33 2942.77    49.4 2940.17
    53.5 2938.81      74 2921.94    82.2 2916.61    86.3 2915.57    94.5 2916.13
   106.8 2921.37   110.9 2921.02     115 2918.36122.7299 2911.06   127.3 2909.38
     156 2909.79162.5998 2911.06   171.7 2911.74   188.8 2911.12     197 2912.66
   201.1 2912.71   225.3 2910.98   229.3 2912.61   261.5 2939.65   269.6 2947.25
   277.6 2952.73   285.7 2960.16   302.5 2970.79   313.4 2974.77   336.3 2984.58
#Mann= 3 ,-1,0
       0      .1       0122.7299    .045       0162.5998      .1       0
#XS Ineff= 2 , 0
                          166.13         2922.21
Permanent Ineff=
       F       F
Bank Sta=122.7299,162.5998
XS Rating Curve= 0 ,0
Exp/Cntr(USF)=0,0
Exp/Cntr=0.3,0.1

Type RM Length L Ch R = 1 ,7138    ,294,297.6,286.5
XS GIS Cut Line= 3
2225690.16497256512291.2437157852225652.24821887512534.191804221
2225659.26983993512628.983688437
#Sta/Elev= 30
       0 2917.88    22.2 2917.12    34.3 2915.13    42.4 2915.01    58.6 2913.41
    66.7 2913.94    70.8 2912.99    74.8 2910.43    78.9 2909.53      87 2909.71
    95.1 2911.64    99.1 2909.51   103.2 2905.15   105.5 2904.13   107.2 2903.36
     112 2903.06   136.5 2904.15   159.8  2906.6   204.4 2907.25   216.5 2908.24
   220.6 2907.94   232.7 2904.08   236.8 2903.59   240.8 2904.27   252.9 2908.73
     277  2924.1     289 2929.19   308.4  2939.5   313.1 2942.23   340.9  2961.3
#Mann= 3 ,-1,0
       0      .1       0   105.5    .045       0   136.5      .1       0
#XS Ineff= 2 , 0
                          218.18         2920.57
Permanent Ineff=
       F       F
Bank Sta=105.5,136.5
XS Rating Curve= 0 ,0
Exp/Cntr(USF)=0,0
Exp/Cntr=0.3,0.1

Type RM Length L Ch R = 1 ,6840    ,222.5,209.1,198.2
XS GIS Cut Line= 3
2225393.82027845512290.645679072 2225399.7865349512521.758472883
  2225443.105376512683.580379792
#Sta/Elev= 30
       0  2897.8    10.5 2897.24    22.5 2895.79    62.6 2897.62    90.6 2897.19
    98.4 2897.93   126.6 2897.31   138.6 2895.79   146.6 2896.06   154.6 2893.65
   166.6 2892.78   174.6 2891.38   182.6 2891.01  200.63 2891.34   210.6 2894.49
   226.6 2894.19   230.6 2895.07   234.7 2896.82     243 2901.43   251.3 2903.54
   267.9 2904.75   280.3  2903.6   305.1 2903.31   309.3 2903.54     316 2905.24
     341 2915.46   346.5 2918.18   371.4 2934.92   392.1 2949.76   398.7  2955.4
#Mann= 3 ,-1,0
       0      .1       0   174.6    .045       0  200.63      .1       0
#XS Ineff= 2 , 0
                          214.42         2896.64
Permanent Ineff=
       F       F
Bank Sta=174.6,200.63
XS Rating Curve= 0 ,0
Exp/Cntr(USF)=0,0
Exp/Cntr=0.3,0.1

Type RM Length L Ch R = 1 ,6631    ,254.3,253.9,253.6
XS GIS Cut Line= 2
2225105.89703098 512382.133831422225356.53883197512731.361407473
#Sta/Elev= 30
       0 2926.21    24.5 2913.23    38.2 2904.16    49.7 2894.26    61.1 2888.31
   102.2 2887.69   118.5 2889.88   129.9 2888.56   141.6 2889.28   146.5 2887.23
   152.9 2881.68   156.4 2880.68     181 2881.69     196 2882.71   215.9 2889.46
   221.7  2889.4   230.2 2886.75     245 2885.72   258.9 2889.49   269.6 2895.72
   274.5  2897.2   310.5 2898.51   318.9 2900.11   338.6 2908.12   358.2 2917.64
   377.9 2929.06   402.2 2946.36   415.5 2953.99   422.3 2961.18   429.9 2967.33
#Mann= 3 ,-1,0
       0      .1       0   152.9    .045       0     181      .1       0
Bank Sta=152.9,181
XS Rating Curve= 0 ,0
Exp/Cntr(USF)=0,0
Exp/Cntr=0.3,0.1

Type RM Length L Ch R = 1 ,6377    ,308.1,303.2,299
XS GIS Cut Line= 2
2224915.40926222512557.5830921172225134.30310176 512844.98569059
#Sta/Elev= 30
       0 2911.48    19.6 2904.53    40.2 2894.18    54.8 2887.84    64.9 2885.24
    79.9 2878.79    85.9 2878.91      95 2880.37   110.1  2879.2     123 2880.33
   128.7 2879.45     143 2875.38   159.7 2874.08   172.9 2874.26   177.2 2875.21
   180.1 2876.75   185.8 2881.36   195.6 2883.65   205.6 2887.73   210.7 2888.83
   230.8 2889.48   251.4  2888.7     261 2890.47     280 2898.05   294.2 2905.63
   308.5 2909.76   318.1 2916.89   326.3 2919.85   339.9 2927.78   361.3 2938.39
#Mann= 3 ,-1,0
       0      .1       0     143    .045       0   177.2      .1       0
Bank Sta=143,177.2
XS Rating Curve= 0 ,0
Exp/Cntr(USF)=0,0
Exp/Cntr=0.3,0.1

Type RM Length L Ch R = 1 ,6074    ,240.7,245.6,248.8
XS GIS Cut Line= 2
2224624.66477307512751.412751552 2224977.2342398513030.460623326
#Sta/Elev= 30
       0 2908.09     4.5 2906.78    14.7 2901.15    35.1 2886.75    54.4 2883.49
    66.4 2879.87    99.5 2875.31     112 2874.77   131.9 2872.14   147.3    2871
   160.4 2871.35   163.2 2870.49   170.4 2865.91   174.6 2865.05   193.2 2865.41
   197.4 2866.09   203.4 2869.07   208.5 2869.93   234.9 2869.55   251.5  2870.1
   267.1 2872.87   279.9 2876.53   299.9 2877.92   315.7 2880.92   320.8 2882.98
   328.4 2887.41   342.6 2897.46   368.2    2913   396.7 2925.64   449.6 2946.21
#Mann= 3 ,-1,0
       0      .1       0   170.4    .045       0   197.4      .1       0
#XS Ineff= 2 , 0
                          220.56         2874.74
Permanent Ineff=
       F       F
Bank Sta=170.4,197.4
XS Rating Curve= 0 ,0
Exp/Cntr(USF)=0,0
Exp/Cntr=0.3,0.1

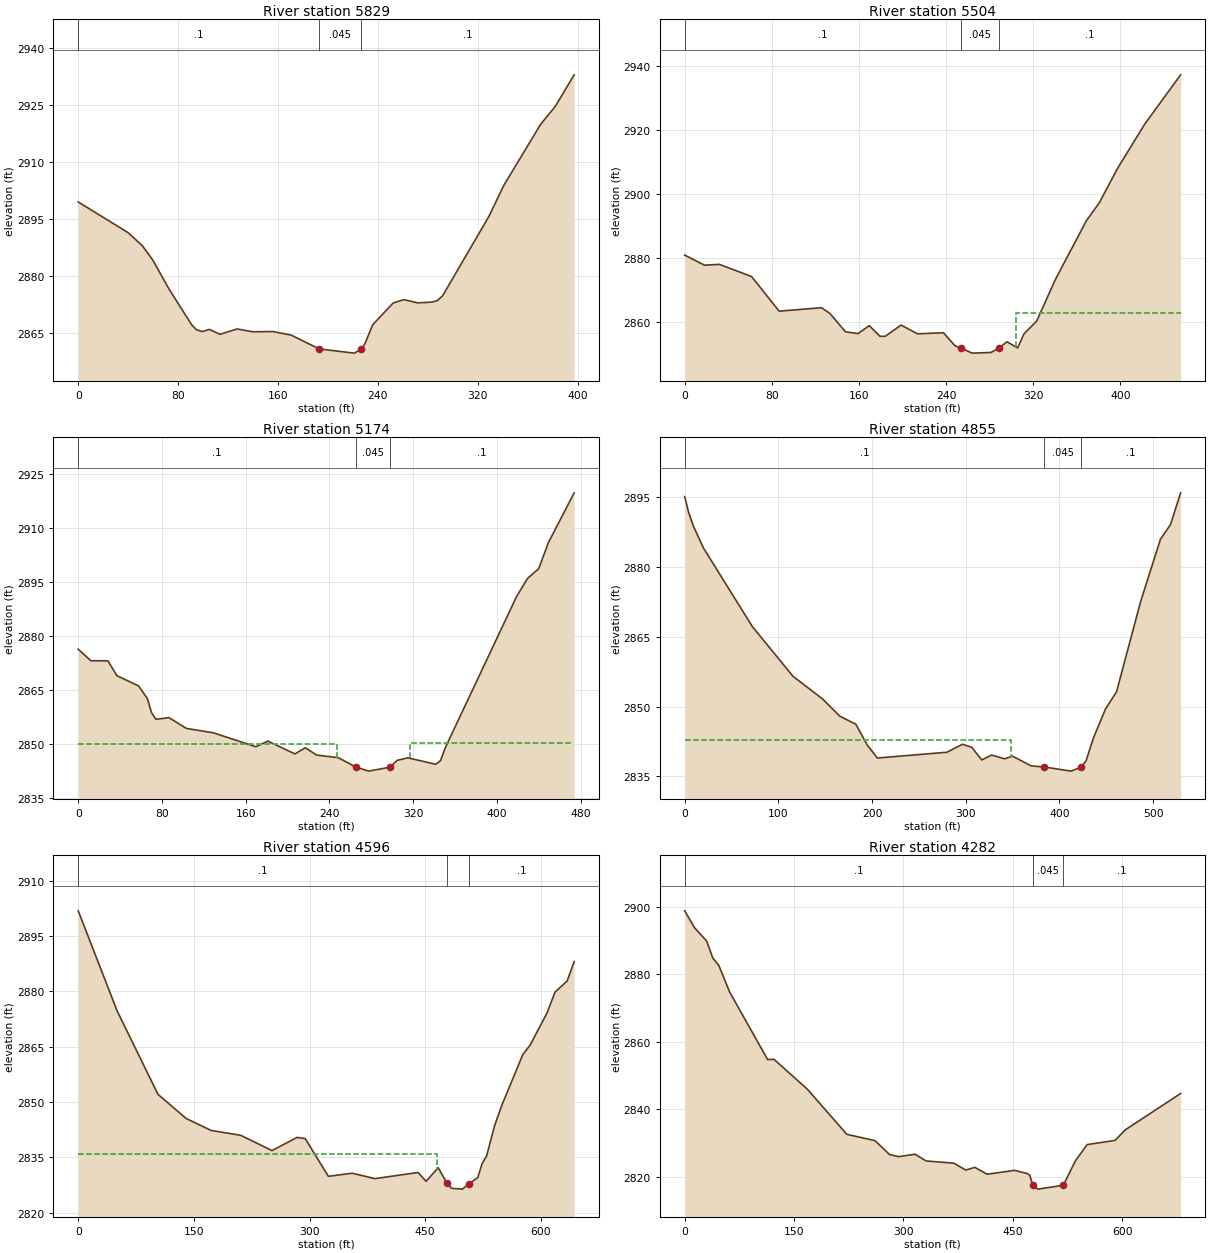
Type RM Length L Ch R = 1 ,5829    ,322,325.1,327.9
XS GIS Cut Line= 2
2224509.36954461512923.5201215692224778.39174434513215.935556062
#Sta/Elev= 30
       0  2899.5      40 2891.42    51.4 2887.97    59.8 2884.18    72.9 2876.51
    90.9 2867.19    94.7 2865.89    99.4  2865.4   105.1 2865.97   113.6 2864.68
   127.3 2866.09     140 2865.34     156 2865.41   170.7 2864.46   193.2 2860.82
   221.1 2859.73   226.8 2860.72   229.6 2862.13     236 2867.23   252.3 2872.91
   260.8  2873.8   272.1 2872.95   283.4 2873.15   287.7 2873.55   291.9  2874.8
   329.1 2895.75   340.9 2903.83   370.4 2919.89   382.3  2924.7   397.3 2932.94
#Mann= 3 ,-1,0
       0      .1       0   193.2    .045       0   226.8      .1       0
Bank Sta=193.2,226.8
XS Rating Curve= 0 ,0
Exp/Cntr(USF)=0,0
Exp/Cntr=0.3,0.1

Type RM Length L Ch R = 1 ,5504    ,323.2,329.7,337.5
XS GIS Cut Line= 2
2224262.06963429513073.9052021652224521.06616199513448.196958317
#Sta/Elev= 30
       0 2881.01    18.2 2877.85    31.8 2878.11    61.4 2874.31    86.7 2863.49
   125.6 2864.57   133.2 2862.81   147.6 2857.05   159.1 2856.47   169.4 2858.97
   179.2 2855.66     184 2855.62   198.6 2859.14   213.7 2856.41   237.5 2856.74
   248.2 2852.66     254 2851.93   263.8 2850.38   281.2 2850.59   288.5 2851.98
   295.8 2853.92   305.6 2852.01   311.5 2856.44     323 2860.34   340.2 2873.35
   368.8  2891.8   380.5 2897.31   397.7 2908.32   422.3 2921.94   455.2 2937.32
#Mann= 3 ,-1,0
       0      .1       0     254    .045       0   288.5      .1       0
#XS Ineff= 2 , 0
                          304.15         2862.98
Permanent Ineff=
       F       F
Bank Sta=254,288.5
XS Rating Curve= 0 ,0
Exp/Cntr(USF)=0,0
Exp/Cntr=0.3,0.1

Type RM Length L Ch R = 1 ,5174    ,324,318.8,306.2
XS GIS Cut Line= 4
2224064.89808418513197.5551573232224150.17438845513506.534843121
2224196.24324418513593.5537928312224237.99409432513629.266929005
#Sta/Elev= 30
       0 2876.33    12.1 2873.13    28.4  2873.1      37 2868.97    57.7 2866.12
      66 2862.66    70.2 2858.62    74.3 2856.85    86.8  2857.3   103.3 2854.33
   129.2 2853.09   169.7 2849.23   181.2 2850.79   207.1 2847.23     217 2848.95
   227.8 2846.92   248.6 2846.17265.09982843.619   277.6 2842.45297.89982843.548
   304.8 2845.44     315 2846.15   341.6 2844.35   346.2 2845.36   350.9 2849.03
   418.8 2890.91   429.4 2896.02     440 2898.69   449.2 2905.89   473.9 2919.79
#Mann= 3 ,-1,0
       0      .1       0265.0998    .045       0297.8998      .1       0
#XS Ineff= 2 ,-1
       0  247.61 2849.96  317.18   473.1 2850.13
Permanent Ineff=
       F       F
Bank Sta=265.0998,297.8998
XS Rating Curve= 0 ,0
Exp/Cntr(USF)=0,0
Exp/Cntr=0.3,0.1

Type RM Length L Ch R = 1 ,4855    ,256.9,259.2,258.1
XS GIS Cut Line= 2
2223665.54214793513378.0172540392224013.09877864 513777.37319029
#Sta/Elev= 30
       0 2895.15     4.2 2891.75     9.5 2888.73    20.1 2884.08    72.2 2867.21
   115.5 2856.53   147.4 2851.59   165.7 2847.91   182.7 2846.19   195.1 2841.65
   205.7 2838.92   279.9 2840.16   296.5 2841.88   306.4 2841.23   317.1 2838.51
   327.7 2839.55   341.5 2838.75     350 2839.32   369.9 2837.23     384 2836.99
   412.4  2836.1   423.1 2836.96   428.4  2838.3   436.6 2843.37   449.2 2849.45
     461 2853.17   486.7 2872.56   507.9    2886   518.6 2889.13   529.4 2895.97
#Mann= 3 ,-1,0
       0      .1       0     384    .045       0   423.1      .1       0
#XS Ineff= 2 , 0
          348.85 2842.84
Permanent Ineff=
       F       F
Bank Sta=384,423.1
XS Rating Curve= 0 ,0
Exp/Cntr(USF)=0,0
Exp/Cntr=0.3,0.1

Type RM Length L Ch R = 1 ,4596    ,306.9,314.1,324.4
XS GIS Cut Line= 3
2223502.64324339 513427.277019222223534.20554425513609.224400683
2223829.40588765513960.122922075
#Sta/Elev= 30
       0 2901.84    50.6 2874.65   103.4 2852.09     140 2845.53   172.4 2842.28
   210.7 2840.97   251.3 2836.83   283.9  2840.4   294.4 2840.08   324.4 2829.85
   355.5 2830.68   384.8 2829.22   440.7 2830.88   451.2 2828.49   466.9 2832.18
   478.4 2827.93   484.1  2826.6   498.2 2826.37   506.8 2827.83   518.2  2829.5
   523.9 2833.34   529.6 2835.32   540.1 2843.63   549.4  2849.1   576.6 2862.86
   586.3  2865.5     608 2874.15   618.5 2879.82   634.1  2882.8   643.2 2888.08
#Mann= 3 ,-1,0
       0      .1       0   478.4    .045       0   506.8      .1       0
#XS Ineff= 2 , 0
          465.35 2835.83
Permanent Ineff=
       F       F
Bank Sta=478.4,506.8
XS Rating Curve= 0 ,0
Exp/Cntr(USF)=0,0
Exp/Cntr=0.3,0.1

Type RM Length L Ch R = 1 ,4282    ,238,236.3,234.2
XS GIS Cut Line= 2
2223308.15889054513508.3290033162223506.24213292 514159.17394259
#Sta/Elev= 30
       0 2898.72    13.5 2893.72    30.2 2889.76    38.5 2884.77    46.9 2882.52
    61.6  2874.7   113.8 2854.65   122.5 2854.73   168.1 2845.91   222.5  2832.5
   261.1 2830.63     281 2826.53   293.6 2825.89     316 2826.61   331.2 2824.62
   369.3 2823.96   385.6 2821.92   398.1 2822.72   414.8 2820.68   452.5 2821.83
   469.2 2820.94   473.4  2820.4   477.5 2817.39   484.7 2816.27   519.4 2817.43
     536 2824.65     552 2829.46   590.4 2830.71   604.5 2833.85   680.3  2844.6
#Mann= 3 ,-1,0
       0      .1       0   477.5    .045       0   519.4      .1       0
Bank Sta=477.5,519.4
XS Rating Curve= 0 ,0
Exp/Cntr(USF)=0,0
Exp/Cntr=0.3,0.1

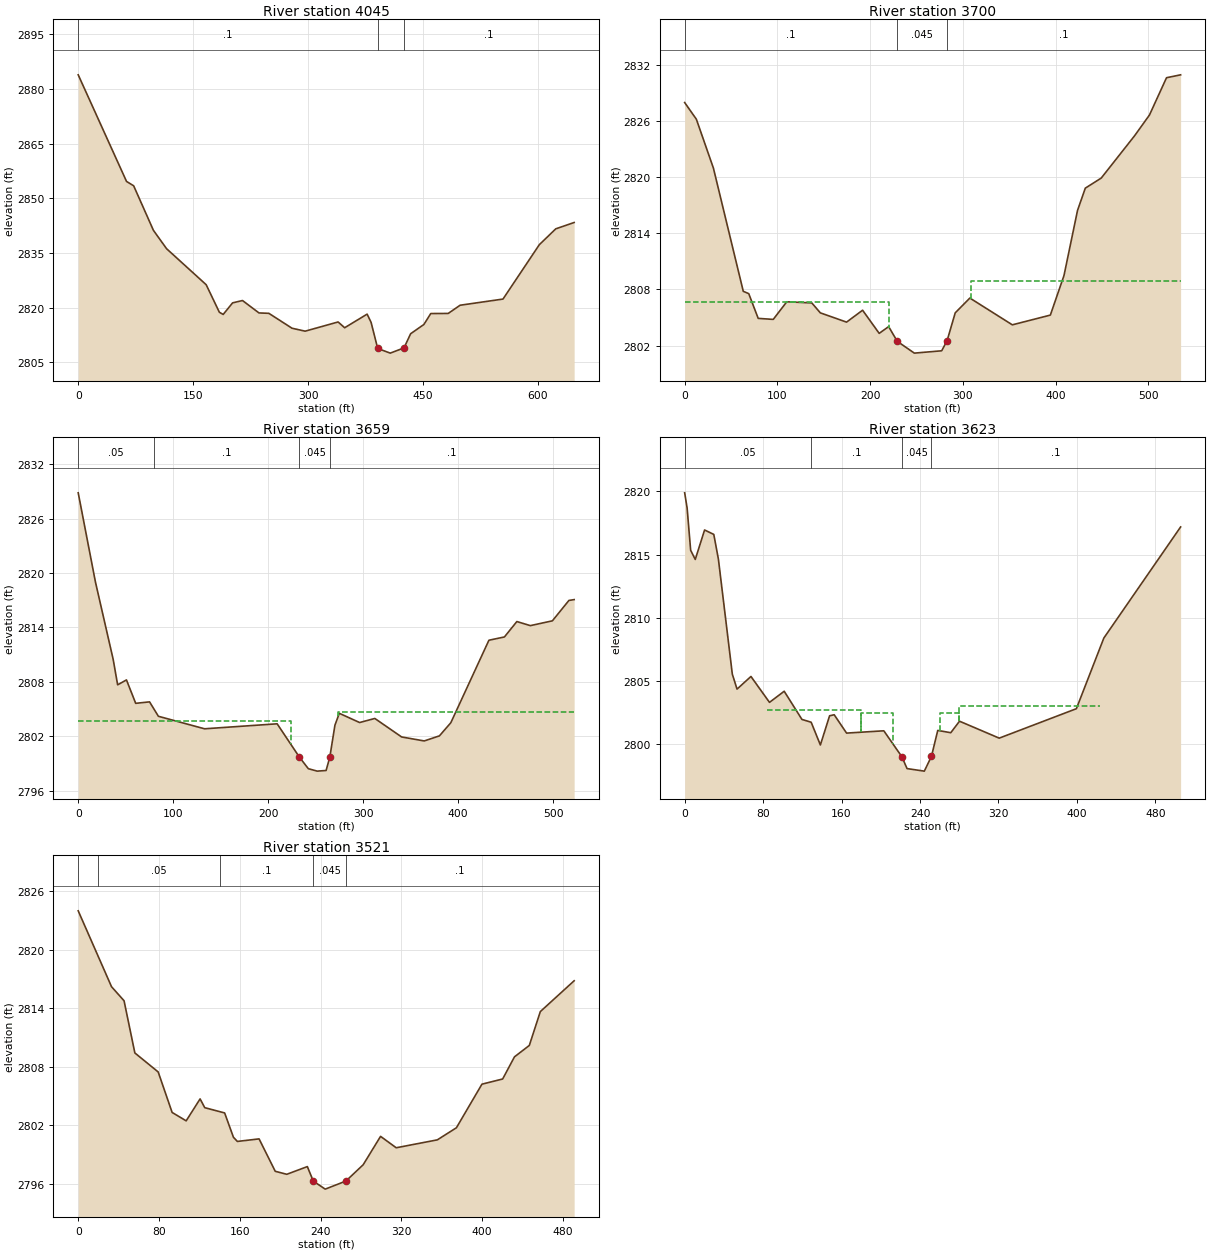
Type RM Length L Ch R = 1 ,4045    ,347.7,345.2,339.8
XS GIS Cut Line= 2
2223077.48048466513677.9188202152223316.98265006514279.459142602
#Sta/Elev= 30
       0 2883.83    63.1  2854.6    72.4 2853.41    98.2  2841.2   115.4 2836.16
   167.1 2826.29   184.3 2818.74   189.3 2818.15   201.6 2821.32   214.5 2821.96
     236 2818.56   248.9 2818.45   279.1 2814.37   296.3 2813.56   339.3 2816.08
   347.9  2814.5   377.2 2818.23   382.4 2815.97     391 2808.82   407.4 2807.54
   425.4 2808.98     434 2812.85   451.3 2815.39   460.3 2818.39   483.1 2818.42
   498.6 2820.67   554.6 2822.36     602 2837.26   623.5 2841.61   647.5 2843.35
#Mann= 3 ,-1,0
       0      .1       0     391    .045       0   425.4      .1       0
Bank Sta=391,425.4
XS Rating Curve= 0 ,0
Exp/Cntr(USF)=0,0
Exp/Cntr=0.3,0.1

Type RM Length L Ch R = 1 ,3700    ,45.9,41.4,38.8
BEGIN DESCRIPTION:
structure xs 4
END DESCRIPTION:
XS GIS Cut Line= 2
 2222792.7637488513970.2742773892223058.76124572514434.355016697
#Sta/Elev= 30
       0 2827.94    12.6 2826.16      31 2820.94    63.2 2807.79    69.1 2807.54
    79.3  2804.9    95.5 2804.79   110.1 2806.67   137.1 2806.55   146.3 2805.49
   174.6  2804.5   191.9 2805.77   209.8  2803.3     220 2804.02   229.3 2802.45
   247.7 2801.19   277.2 2801.44     283 2802.51   291.8 2805.49   307.6 2807.07
   353.4 2804.21   394.4 2805.25   409.1 2809.47   423.7 2816.42   432.1  2818.8
   449.3 2819.88   485.3  2824.4   501.3 2826.61   519.7 2830.59   534.9  2830.9
#Mann= 3 ,-1,0
       0      .1       0   229.3    .045       0     283      .1       0
#XS Ineff= 2 , 0
          220.73 2806.69  308.96         2808.86
Permanent Ineff=
       F       F
Bank Sta=229.3,283
XS Rating Curve= 0 ,0
Exp/Cntr(USF)=0,0
Exp/Cntr=0.5,0.3

Type RM Length L Ch R = 1 ,3659    ,35.3,35.5,36.4
BEGIN DESCRIPTION:
structure xs 3; 9 ft between structure and xs
END DESCRIPTION:
XS GIS Cut Line= 6
2222744.83663087514025.5598381742222805.79746497514127.494347654
2222872.75444668 514189.454539692222910.73004825514253.413447599
 2222903.7345427 514421.305580862222940.71078634514480.267699088
#Sta/Elev= 30
       0 2828.84    18.2 2818.97    36.8 2810.47    41.5 2807.66    50.8  2808.2
    60.5 2805.62    75.1 2805.78    84.4 2804.19     133 2802.81   209.4 2803.36
   232.9 2799.67   242.2 2798.41   251.5 2798.14   260.9 2798.21   264.8 2799.67
   270.2  2803.2   274.8 2804.52   296.2  2803.5   312.2 2803.95   340.4 2801.91
   364.2 2801.47   380.2 2802.03   392.2 2803.48   432.3 2812.58   448.6 2812.94
   461.7 2814.64   475.9 2814.19   499.1 2814.72   516.5 2816.97     522 2817.06
#Mann= 4 ,-1,0
       0     .05       0      80      .1       0   232.9    .045       0
   264.8      .1       0
#XS Ineff= 2 , 0
           223.9  2803.7   273.8          2804.7
Permanent Ineff=
       F       F
Bank Sta=232.9,264.8
XS Rating Curve= 0 ,0
Exp/Cntr(USF)=0,0
Exp/Cntr=0.5,0.3

Type RM Length L Ch R = 1 ,3623    ,102.6,102.4,102.1
BEGIN DESCRIPTION:
structure xs 2; 9 ft between structure and xs
END DESCRIPTION:
XS GIS Cut Line= 6
2222713.85653485514060.0376869692222766.82250546514143.983753599
 2222828.7826975 514181.959355172222875.75252049  514265.9054218
2222868.75701494 514433.797555062222905.73325857514492.759673289
#Sta/Elev= 30
       0 2819.89     2.5 2818.68     6.1 2815.34    10.8 2814.62    20.3 2816.95
    29.7  2816.6    34.4 2814.64    48.6 2805.54    53.4 2804.36    67.6 2805.36
    86.5 2803.31   101.5 2804.19   119.6 2801.96     129 2801.74   138.4 2799.94
   147.8 2802.25   152.5 2802.33   165.1 2800.88   203.1 2801.06   221.5 2799.01
   226.8 2798.07   244.4 2797.87  251.692799.036   258.1 2801.09   271.4 2800.91
   280.3 2801.82   320.8 2800.48   399.5 2802.81   427.5  2808.4   505.8 2817.19
#Mann= 4 ,-1,0
       0     .05       0  129.26      .1       0   221.5    .045       0
  251.69      .1       0
#XS Ineff= 4 ,-1
   83.49  180.17 2802.72  180.17   212.5 2802.45   260.7  280.23 2802.45
  280.23  423.21 2803.02
Permanent Ineff=
       F       F       F       F
Bank Sta=221.5,251.69
XS Rating Curve= 0 ,0
Exp/Cntr(USF)=0,0
Exp/Cntr=0.5,0.3

Type RM Length L Ch R = 1 ,3521    ,63.7,63.3,63.5
BEGIN DESCRIPTION:
structure xs 1
END DESCRIPTION:
XS GIS Cut Line= 2
2222646.89955313 514072.529661172222891.74224747514498.256141937
#Sta/Elev= 30
       0    2824      33 2816.22    45.4 2814.78    56.1 2809.43    79.2 2807.48
      93 2803.33   106.9 2802.47   120.7 2804.72   125.3 2803.82     145 2803.28
   153.7 2800.79   157.6 2800.36   179.1 2800.62   195.1  2797.3   206.5 2796.99
   226.9 2797.78   232.8 2796.29   244.6 2795.47   265.1  2796.3   282.2 2797.97
   299.4 2800.88   314.9 2799.71   355.6 2800.52   374.5 2801.76   399.8 2806.23
   420.3 2806.76     432 2809.03   446.7  2810.2   457.6 2813.67   491.1 2816.83
#Mann= 5 ,-1,0
       0      .1       0      20     .05       0     140      .1       0
   232.8    .045       0   265.1      .1       0
Bank Sta=232.8,265.1
XS Rating Curve= 0 ,0
Exp/Cntr(USF)=0,0
Exp/Cntr=0.3,0.1