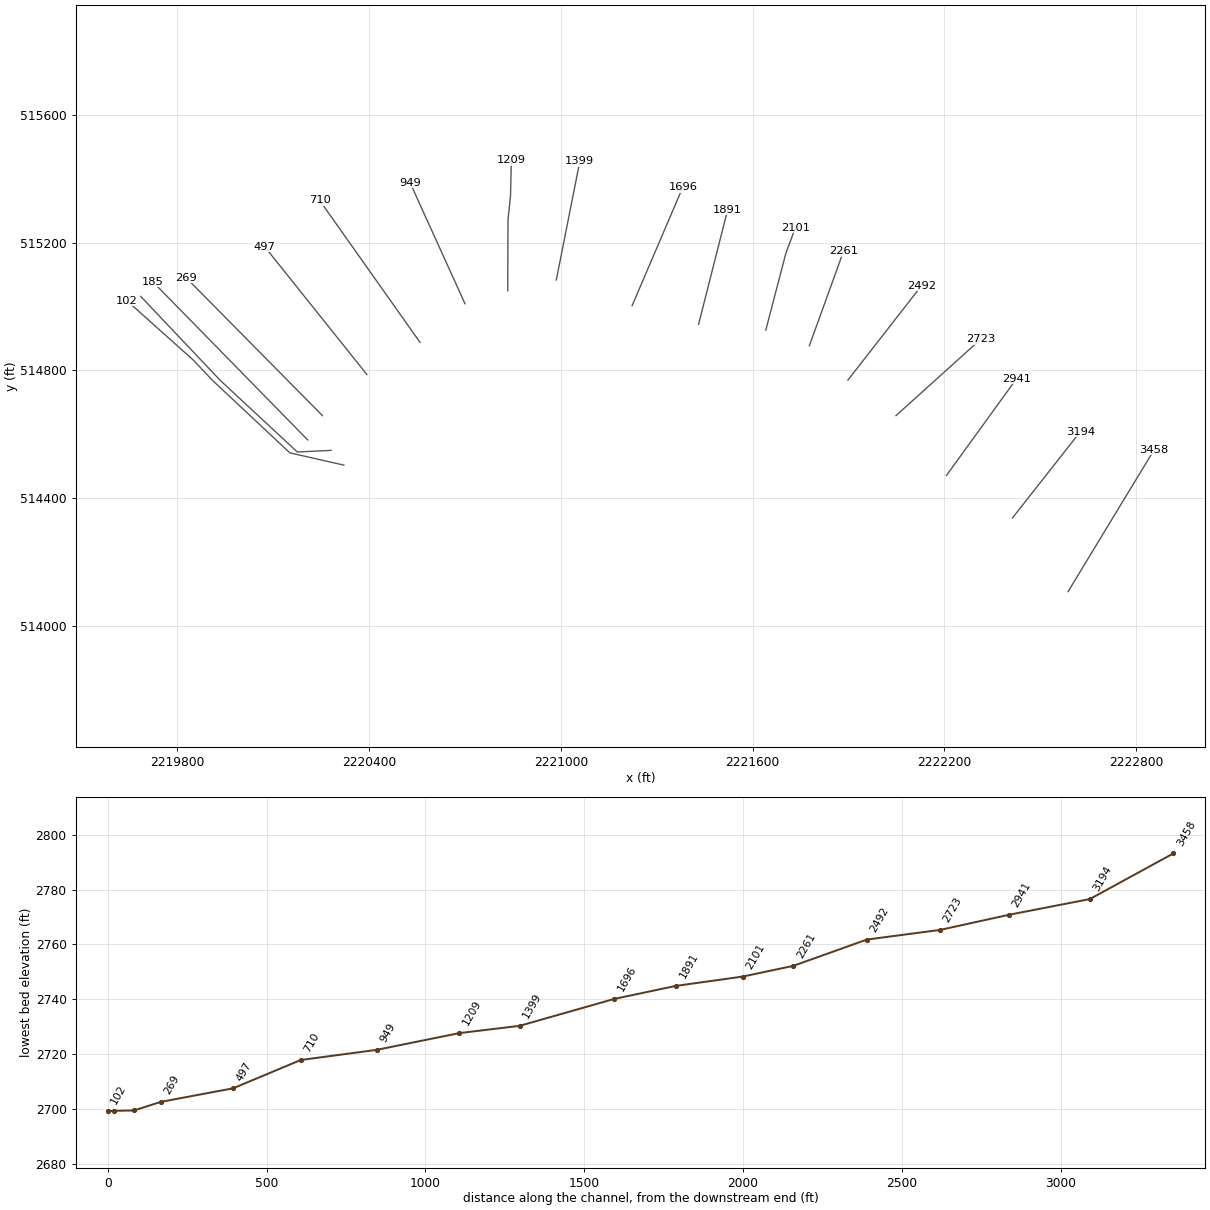
HEC-RAS study SLTYFK.prj: SLTYFK

--- SLTYFK.g01 (geometry) --- (continued)

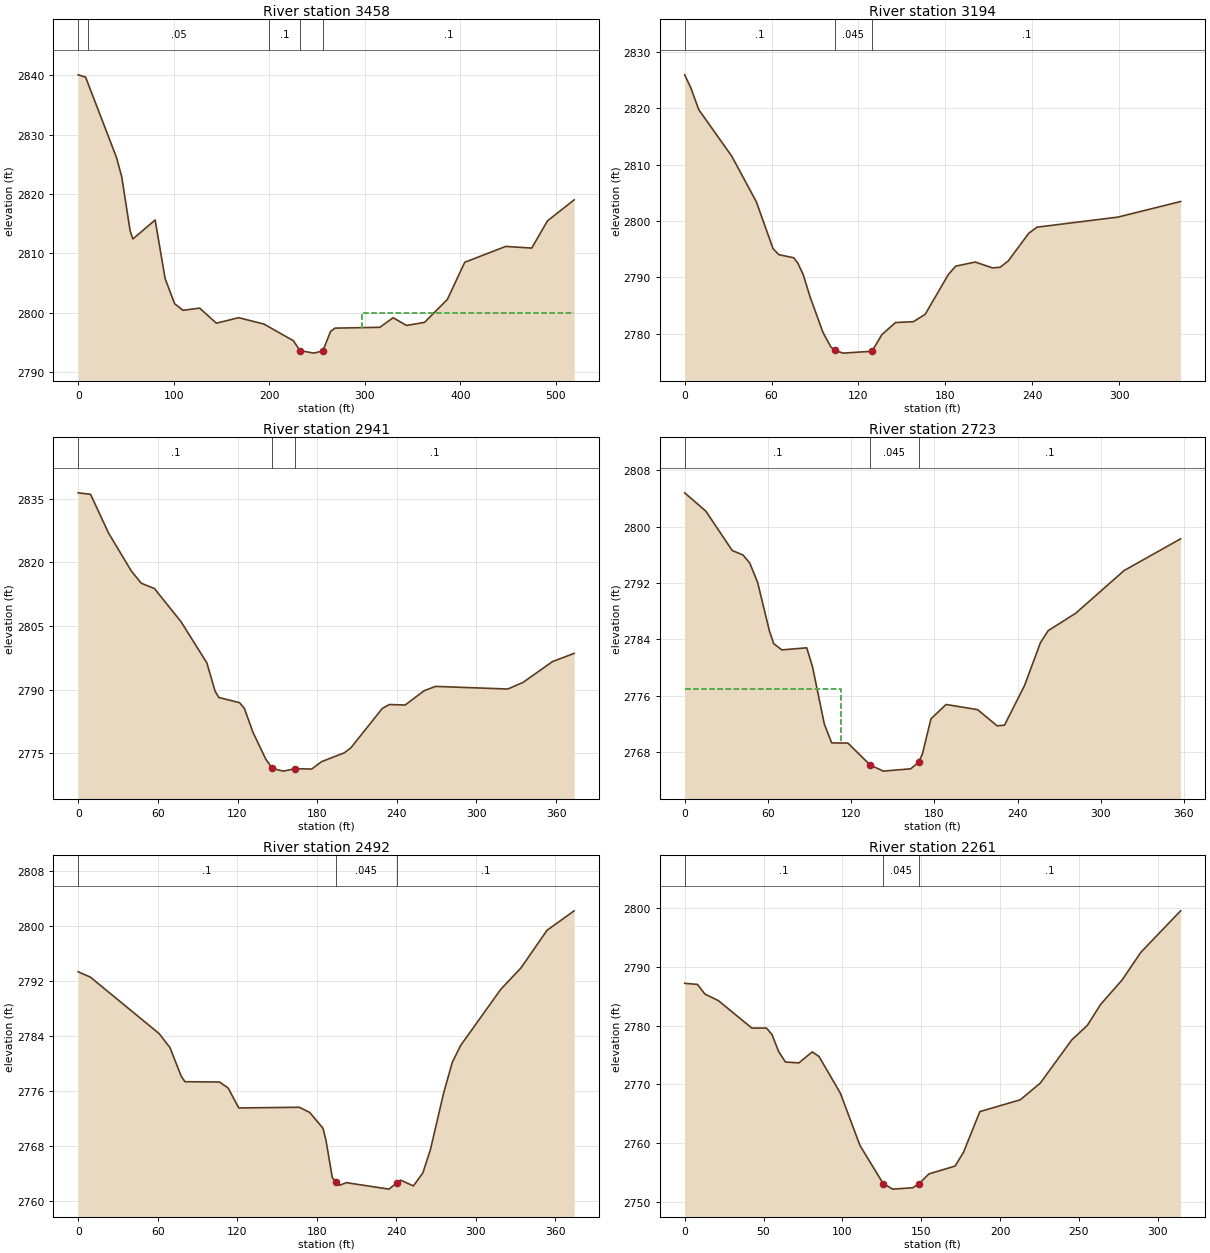
Type RM Length L Ch R = 1 ,3458    ,266.2,263.5,262
XS GIS Cut Line= 2
2222587.39000607514107.380535637 2222856.5978664514551.109353694
#Sta/Elev= 30
       0 2840.07     7.7 2839.69    40.1 2826.14    45.6 2822.86    54.3 2813.82
    57.2 2812.43    80.5 2815.62      91 2805.73   100.9 2801.52   109.6 2800.41
   127.1 2800.78   144.6 2798.24   167.9 2799.17   194.3  2798.1   225.2 2795.29
   231.9 2793.64   246.5  2793.2     256 2793.57   264.1 2796.86   268.8 2797.41
   315.6 2797.55   329.6 2799.16   343.6 2797.86   362.4 2798.38   386.3 2802.24
   404.5  2808.5   447.4 2811.17   474.6 2810.89   491.1 2815.48     519 2819.01
#Mann= 5 ,-1,0
       0      .1       0      10     .05       0     200      .1       0
   231.9    .045       0     256      .1       0
#XS Ineff= 2 , 0
                          297.13         2799.96
Permanent Ineff=
       F       F
Bank Sta=231.9,256
XS Rating Curve= 0 ,0
Exp/Cntr(USF)=0,0
Exp/Cntr=0.3,0.1

Type RM Length L Ch R = 1 ,3194    ,252.9,253.4,253.6
XS GIS Cut Line= 2
2222413.57959804514338.1064949752222625.23267443514607.314355302
#Sta/Elev= 30
       0 2825.92     4.2 2823.64     9.7 2819.75    32.5 2811.49    49.5 2803.38
      61 2795.09      65 2794.01    75.3 2793.46    78.1 2792.52    81.9 2790.43
    86.6 2786.51    95.5  2780.2   100.9 2777.65   103.7 2777.03   109.4 2776.54
   129.32776.867   136.2 2779.84   145.6 2781.97   157.9 2782.12     166 2783.41
     182 2790.47   187.1 2791.97   200.6  2792.7   212.5 2791.67   217.8 2791.77
   223.4  2792.9   237.6 2797.82   243.3 2798.89     299 2800.67   342.4 2803.44
#Mann= 3 ,-1,0
       0      .1       0   103.7    .045       0   129.3      .1       0
Bank Sta=103.7,129.3
XS Rating Curve= 0 ,0
Exp/Cntr(USF)=0,0
Exp/Cntr=0.3,0.1

Type RM Length L Ch R = 1 ,2941    ,221,218.1,216
XS GIS Cut Line= 2
2222206.73230195514470.6895537312222425.81180208514773.316320857
#Sta/Elev= 30
       0  2836.4     9.3 2836.05    22.9  2826.9    40.1 2817.94    47.5  2815.1
    57.4 2813.86    77.5 2806.02    96.9 2796.35   103.1  2789.7   105.9 2788.19
   121.6 2786.96   125.2 2785.59   131.7 2779.95   141.3 2773.66   146.3 2771.46
   154.6 2770.84   163.2 2771.42   175.9 2771.33   183.3 2773.07   200.6 2775.17
   205.5 2776.37   229.1 2785.61   234.4 2786.53   246.3 2786.41   260.6 2789.78
   269.2  2790.8   323.6 2790.18   335.1 2791.74   357.2 2796.63   373.6 2798.58
#Mann= 3 ,-1,0
       0      .1       0   146.3    .045       0   163.2      .1       0
Bank Sta=146.3,163.2
XS Rating Curve= 0 ,0
Exp/Cntr(USF)=0,0
Exp/Cntr=0.3,0.1

Type RM Length L Ch R = 1 ,2723    ,218.5,230.4,229.5
XS GIS Cut Line= 2
2222048.92079762514658.2067529932222314.41544608514897.708918388
#Sta/Elev= 30
       0  2804.8    15.2 2802.21    34.3 2796.61    42.1 2795.97    46.9 2794.84
    52.6 2792.08    61.1  2785.2    64.2 2783.38    70.1  2782.5      88  2782.8
    92.2 2780.09   100.7 2771.97     106  2769.3   117.7 2769.27   133.7 2766.17
   143.2 2765.29     163 2765.62   168.7 2766.56   171.4 2767.72   177.6 2772.72
   188.5 2774.75   211.2 2774.02   225.3 2771.72   230.6 2771.81   245.1 2777.46
   256.5 2783.52   262.1 2785.23     282 2787.71   316.8 2793.76   357.6 2798.27
#Mann= 3 ,-1,0
       0      .1       0   133.7    .045       0   168.7      .1       0
#XS Ineff= 2 , 0
          113.06 2776.91
Permanent Ineff=
       F       F
Bank Sta=133.7,168.7
XS Rating Curve= 0 ,0
Exp/Cntr(USF)=0,0
Exp/Cntr=0.3,0.1

Type RM Length L Ch R = 1 ,2492    ,214,231.4,234.1
XS GIS Cut Line= 2
2221898.53571702514769.6031089912222128.75485275515064.803452384
#Sta/Elev= 30
       0 2793.35     9.2 2792.57    61.2 2784.35    69.3 2782.32    77.8 2778.16
    80.6 2777.38   106.7 2777.34   113.2 2776.46   121.2 2773.57   166.9 2773.67
   174.7 2772.93   184.8 2770.62   187.1 2768.82   191.8 2763.48   194.7 2762.75
   197.3 2762.34   202.4 2762.72   234.6 2761.78   240.3 2762.64   243.3 2763.09
   253.1 2762.25   260.2 2764.15   265.9 2767.52   275.8 2775.68   282.4  2780.2
   288.7 2782.64     319  2790.8   334.3 2793.92   353.9 2799.37   374.4  2802.2
#Mann= 3 ,-1,0
       0      .1       0   194.7    .045       0   240.3      .1       0
Bank Sta=194.7,240.3
XS Rating Curve= 0 ,0
Exp/Cntr(USF)=0,0
Exp/Cntr=0.3,0.1

Type RM Length L Ch R = 1 ,2261    ,157.3,159.6,165.8
XS GIS Cut Line= 2
2221777.85633136514877.1005925292221884.79683311515172.857917702
#Sta/Elev= 30
       0 2787.18     8.1 2786.99    12.8 2785.36    21.4 2784.23    42.6 2779.57
    51.9 2779.57    55.4 2778.45    59.6 2775.57    63.9  2773.8    72.4 2773.65
    80.9 2775.52    85.2 2774.74    98.7 2768.52   111.2 2759.59  125.892753.135
   131.9 2752.19   144.7 2752.43   148.7 2753.13   154.9 2754.78   171.5 2756.11
   176.8 2758.45   187.2 2765.37   212.8 2767.37   225.5 2770.21   245.5 2777.57
   255.3 2780.01   263.8  2783.6   277.4 2787.75   289.3 2792.45   314.5  2799.5
#Mann= 3 ,-1,0
       0      .1       0  125.89    .045       0   148.7      .1       0
Bank Sta=125.89,148.7
XS Rating Curve= 0 ,0
Exp/Cntr(USF)=0,0
Exp/Cntr=0.3,0.1

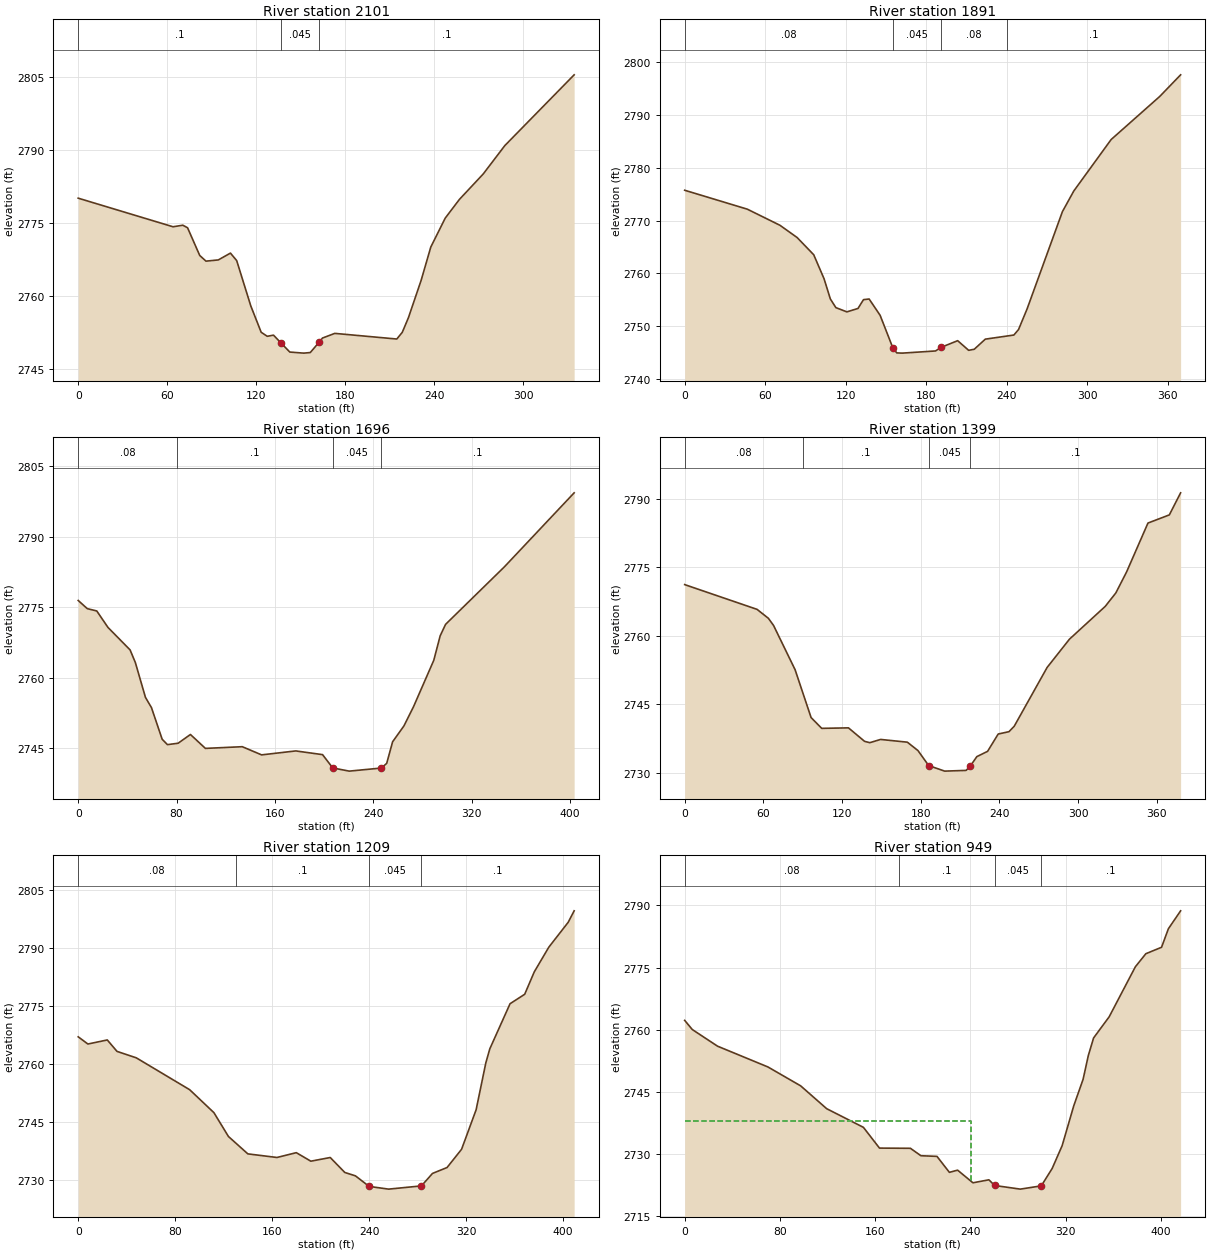
Type RM Length L Ch R = 1 ,2101    ,210,210.3,211.6
XS GIS Cut Line= 3
2221641.48021163514925.8917708922221704.67480111515167.747607164
2221734.32164556515246.545798981
#Sta/Elev= 30
       0 2780.15    63.9 2774.27    70.5 2774.59    73.7 2774.06    81.9 2768.36
    86.1  2767.2    94.4 2767.45   102.6 2768.85   106.8 2767.31   116.3 2757.99
   123.3 2752.57   127.4 2751.74   131.6 2751.98   136.8 2750.32   142.6  2748.5
   151.9 2748.28   156.4  2748.4   162.2 2750.48   164.6 2751.38   172.9 2752.34
   214.7 2751.18   218.4 2752.57   222.5 2755.55   231.1 2763.26   237.6  2770.1
   247.3 2776.04   256.9  2779.9   272.9 2785.12   287.5 2790.97   334.2 2805.52
#Mann= 3 ,-1,0
       0      .1       0   136.8    .045       0   162.2      .1       0
Bank Sta=136.8,162.2
XS Rating Curve= 0 ,0
Exp/Cntr(USF)=0,0
Exp/Cntr=0.3,0.1

Type RM Length L Ch R = 1 ,1891    ,197.7,194.4,186.5
XS GIS Cut Line= 2
2221431.14947951 514943.94602823  2221522.068376515302.308511099
#Sta/Elev= 30
       0 2775.76    46.7 2772.17      71 2769.12    83.8  2766.8    96.2 2763.53
   103.9 2758.98   108.6 2755.15   112.7 2753.51   120.9  2752.7   129.2 2753.35
   133.3 2755.02   137.5 2755.14   145.7 2752.05   155.1 2745.93   158.1 2744.92
   162.2 2744.88     187 2745.29   191.1 2745.97   203.5 2747.24   211.7 2745.41
   215.9 2745.62   224.1 2747.53   245.4 2748.31   248.9 2749.36   255.3 2753.29
   281.6 2771.71   290.1 2775.63   317.9 2785.37   354.1 2793.53   369.7 2797.64
#Mann= 4 ,-1,0
       0     .08       0   155.1    .045       0   191.1     .08       0
     240      .1       0
Bank Sta=155.1,191.1
XS Rating Curve= 0 ,0
Exp/Cntr(USF)=0,0
Exp/Cntr=0.3,0.1

Type RM Length L Ch R = 1 ,1696    ,293.3,297.7,303.5
XS GIS Cut Line= 2
2221223.10247849515002.4214930262221381.84228578515373.371358498
#Sta/Elev= 30
       0 2776.45     7.4 2774.71    15.1 2774.22    24.2 2770.72    42.2 2765.93
    46.5 2763.23    54.7 2755.83    59.6 2753.64    68.3 2746.91    72.6 2745.76
    81.3 2746.06    91.3 2747.92   103.5 2744.96   133.5 2745.32   149.2 2743.58
     177 2744.42   198.8 2743.63   207.1  2740.8   220.5 2740.12   246.7 2740.78
   246.7 2740.79     251 2741.78   255.8 2746.37     265 2749.74   272.8 2753.83
   289.3 2763.72   294.5 2768.93   298.9 2771.37   346.7  2783.6   403.5 2799.37
#Mann= 4 ,-1,0
       0     .08       0      80      .1       0   207.1    .045       0
   246.7      .1       0
Bank Sta=207.1,246.7
XS Rating Curve= 0 ,0
Exp/Cntr(USF)=0,0
Exp/Cntr=0.3,0.1

Type RM Length L Ch R = 1 ,1399    ,187.1,189.4,191.4
XS GIS Cut Line= 2
2220985.82824021515082.6268693442221059.34983517515453.576734816
#Sta/Elev= 30
       0 2771.22    55.2 2765.79    63.8 2763.84    67.8 2762.25    84.2 2752.56
    96.4 2742.06   104.5 2739.69   124.9  2739.8   137.2 2736.84   141.2 2736.55
   149.4 2737.26   169.8 2736.66   177.9 2734.82   186.1 2731.52   198.3 2730.31
   214.6 2730.47   217.8 2731.42   222.8 2733.49     231 2734.65   239.1 2738.45
   247.3 2738.96   251.3 2740.15   276.4 2753.05   293.4 2759.24   320.7 2766.44
   328.8 2769.39     337    2774   353.3 2784.72   369.6 2786.51   378.2 2791.35
#Mann= 4 ,-1,0
       0     .08       0      90      .1       0   186.1    .045       0
   217.8      .1       0
Bank Sta=186.1,217.8
XS Rating Curve= 0 ,0
Exp/Cntr(USF)=0,0
Exp/Cntr=0.3,0.1

Type RM Length L Ch R = 1 ,1209    ,247.3,260.9,274.6
XS GIS Cut Line= 4
2220833.77221428515049.2079625452220834.67866292515271.192685347
2220842.45144686515344.4789339922220845.22278779515458.018325643
#Sta/Elev= 30
       0 2767.03       8 2765.17      24 2766.22      32 2763.27      48 2761.59
      92 2753.36     112 2747.43     124 2741.27     140 2736.78     164 2735.85
     180 2737.09     192 2734.89     208 2735.84     220 2731.98   228.8  2731.1
   240.1 2728.37   256.2 2727.67   283.3 2728.51   292.4 2731.73   304.4 2733.25
   316.4 2737.97   328.4 2748.18   336.4 2760.29   339.7 2763.93   356.4 2775.58
   368.5 2778.03   376.4 2783.82   388.4  2790.2   404.4 2796.63   409.3 2799.59
#Mann= 4 ,-1,0
       0     .08       0     130      .1       0   240.1    .045       0
   283.3      .1       0
Bank Sta=240.1,283.3
XS Rating Curve= 0 ,0
Exp/Cntr(USF)=0,0
Exp/Cntr=0.3,0.1

Type RM Length L Ch R = 1 ,949     ,234,238.9,244.7
XS GIS Cut Line= 2
2220700.03240172515008.501936514 2220527.9250317515387.806528686
#Sta/Elev= 30
       0 2762.27     6.4 2760.06    27.6 2756.04    69.9 2751.03    97.4 2746.47
   119.3 2740.95   150.1 2736.46   163.6 2731.45   189.6  2731.4   198.4 2729.61
   211.9 2729.45   222.3  2725.6   229.2 2726.13   242.1 2723.08   255.5  2723.8
   260.3 2722.43   281.9 2721.55   299.5 2722.34   308.6 2726.52     317 2732.03
   326.7  2741.6   334.6 2748.05     339 2753.79   343.4 2758.02   356.5 2763.13
   378.5  2775.2   387.3 2778.35   400.5 2779.91   406.2 2784.36   416.5  2788.7
#Mann= 4 ,-1,0
       0     .08       0     180      .1       0   260.3    .045       0
   299.5      .1       0
#XS Ineff= 2 , 0
           240.4 2737.89
Permanent Ineff=
       F       F
Bank Sta=260.3,299.5
XS Rating Curve= 0 ,0
Exp/Cntr(USF)=0,0
Exp/Cntr=0.3,0.1

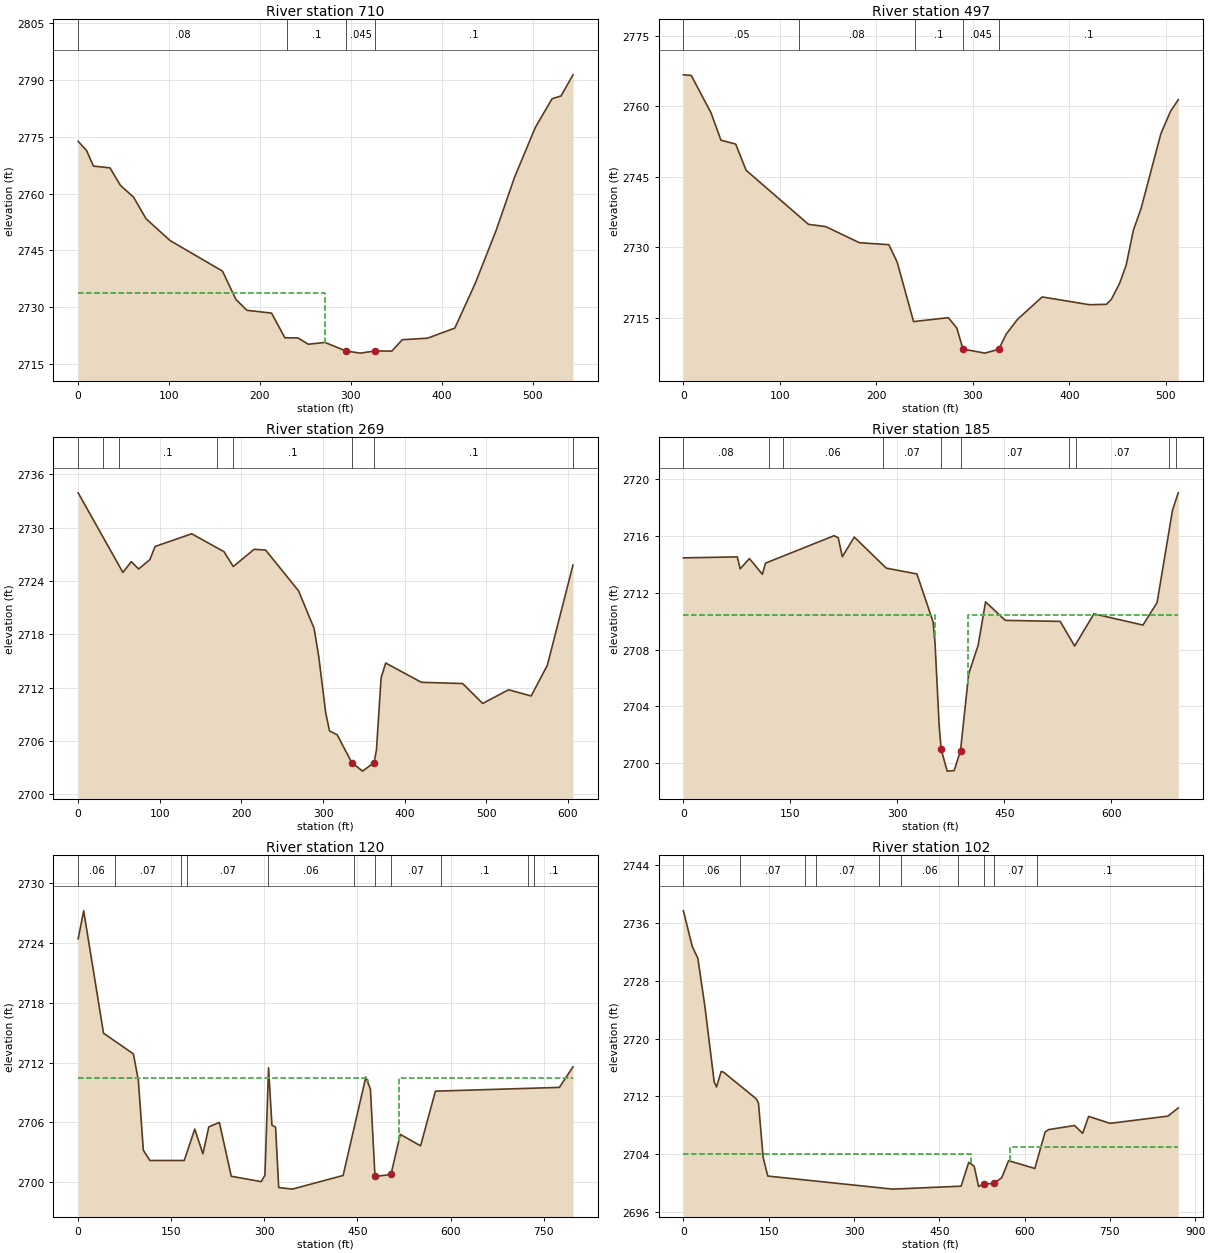
Type RM Length L Ch R = 1 ,710     ,211.2,212.9,213.5
XS GIS Cut Line= 2
2220559.30092247514887.4641042612220245.16319856515331.935564692
#Sta/Elev= 30
       0 2773.79     9.2 2771.38    16.8 2767.25      35 2766.79    46.5 2762.16
    60.9 2759.07    74.7 2753.34     101  2747.6   158.8  2739.5   173.5 2732.04
   185.6 2729.16   212.7 2728.42   227.4  2721.9   241.7 2721.87   253.2  2720.2
   271.5 2720.67   294.8  2718.4   310.4 2717.85  326.39 2718.43     345 2718.38
   356.5  2721.4   384.2 2721.79   414.3 2724.46   436.8 2736.29   459.8  2750.3
   479.9 2764.24   502.8 2777.44   521.3 2785.06   531.1 2785.77   544.3 2791.36
#Mann= 4 ,-1,0
       0     .08       0     230      .1       0   294.8    .045       0
  326.39      .1       0
#XS Ineff= 2 , 0
          271.77 2733.78
Permanent Ineff=
       F       F
Bank Sta=294.8,326.39
XS Rating Curve= 0 ,0
Exp/Cntr(USF)=0,0
Exp/Cntr=0.3,0.1

Type RM Length L Ch R = 1 ,497     ,226.2,227.2,228.9
XS GIS Cut Line= 2
2220393.08551901514786.816056372 2220072.8673516 515187.29308789
#Sta/Elev= 30
       0 2766.67     8.1 2766.55    28.6  2758.6    38.9 2752.78    54.2 2751.95
    64.9  2746.4   129.6  2734.9   147.5 2734.42   182.3    2731   212.9 2730.57
   221.5 2726.88   238.5 2714.23   274.5 2715.07   283.3 2712.86   289.7 2708.39
   312.5 2707.53   326.8 2708.36   334.5 2711.56   346.2 2714.71   371.8 2719.47
   420.7 2717.82   438.4  2717.9   443.5 2718.97     452 2722.36   458.8 2726.22
   466.2 2733.58   474.2 2738.23   494.8 2754.17   504.9 2758.96   512.8 2761.39
#Mann= 5 ,-1,0
       0     .05       0     120     .08       0     240      .1       0
   289.7    .045       0   326.8      .1       0
Bank Sta=289.7,326.8
XS Rating Curve= 0 ,0
Exp/Cntr(USF)=0,0
Exp/Cntr=0.3,0.1

Type RM Length L Ch R = 1 ,269     ,84.8,84.7,84.6
BEGIN DESCRIPTION:
structure xs 4
END DESCRIPTION:
XS GIS Cut Line= 2
2220253.95418131514658.2067529932219827.86311962515089.310650704
#Sta/Elev= 30
       0 2733.92    54.8 2724.96    65.1 2726.17    74.1 2725.35    87.9 2726.41
    94.2 2727.88   139.1 2729.31   178.7 2727.29     190 2725.62   215.5 2727.56
   229.6 2727.48     270 2722.88     289 2718.66   294.7 2715.49   303.2 2709.17
   307.9 2707.12   317.3 2706.68  335.252703.529   348.4 2702.59   362.6 2703.56
   365.4 2705.01   371.1  2713.1   376.7 2714.76   420.4 2712.59     471 2712.45
   495.5 2710.21   527.2 2711.75   554.9 2711.05   574.7  2714.5   606.1 2725.79
#Mann= 8 ,-1,0
       0      .1       0      30     .05       0      50      .1       0
     170     .08       0     190      .1       0  335.25    .045       0
   362.6      .1       0  606.14     .06       0
Bank Sta=335.25,362.6
XS Rating Curve= 0 ,0
Exp/Cntr(USF)=0,0
Exp/Cntr=0.5,0.3

Type RM Length L Ch R = 1 ,185     ,64.8,64.4,64.4
BEGIN DESCRIPTION:
structure xs 3; 9.9 ft between structure and xs
END DESCRIPTION:
XS GIS Cut Line= 2
2220207.90125679514582.076812359 2219722.5935632515077.614033324
#Sta/Elev= 30
       0 2714.44    75.5 2714.51    79.6 2713.67    92.5 2714.39   110.7 2713.29
   115.1 2714.07   211.3    2716     217 2715.85   222.7 2714.52   239.5  2715.9
   284.3 2713.72   327.3 2713.31   349.9 2709.95   352.7 2708.44   358.4 2702.73
   361.2 2701.01   369.7 2699.46   379.5  2699.5   388.4  2700.9   399.8 2706.28
   413.1  2708.3   423.5 2711.35   451.2 2710.05   528.1 2709.98   548.4 2708.25
   575.4 2710.51   644.1 2709.72   663.9  2711.3   685.6 2717.81   693.6 2719.01
#Mann= 10 ,-1,0
       0     .08       0     120     .07       0     140     .06       0
     280     .07       0   361.2    .045       0   388.4     .07       0
     540      .1       0     550     .07       0     680      .1       0
     690     .07       0
#XS Ineff= 2 , 0
           352.2 2710.42   398.3         2710.42
Permanent Ineff=
       F       F
Bank Sta=361.2,388.4
XS Rating Curve= 0 ,0
Exp/Cntr(USF)=0,0
Exp/Cntr=0.5,0.3

Type RM Length L Ch R = 1 ,120     ,17.8,18.3,23.4
BEGIN DESCRIPTION:
structure xs 2; 30.2 ft between structure and xs
END DESCRIPTION:
XS GIS Cut Line= 4
2220281.05271438514549.4943331652220175.40271911514544.376478301
2219934.35758492514768.3325917752219685.11609727515031.540221993
#Sta/Elev= 30
       0  2724.4     8.9 2727.21    40.9 2714.94      89 2712.87      97 2710.21
     105 2703.21   115.6 2702.18   170.9 2702.18   187.9 2705.33     201 2702.85
   210.5 2705.55   227.5    2706   246.7  2700.6     295 2700.06   300.9 2700.71
   306.8 2711.47   312.2 2705.72   318.1 2705.52   323.1 2699.47     345 2699.31
   426.9 2700.68   463.5 2710.55   470.9 2709.32  478.272700.578  504.022700.781
     519  2704.8   551.7 2703.65   575.6 2709.13   775.4 2709.51   797.3 2711.57
#Mann= 11 ,-1,0
       0     .06       0      60     .07       0  165.77     .08       0
  175.77     .07       0  305.77     .06       0   444.8     .07       0
  478.27    .045       0  504.02     .07       0   584.8      .1       0
   724.8     .07       0   734.8      .1       0
#XS Ineff= 2 , 0
           466.7 2710.42   516.5         2710.42
Permanent Ineff=
       F       F
Bank Sta=478.27,504.02
XS Rating Curve= 0 ,0
Exp/Cntr(USF)=0,0
Exp/Cntr=0.5,0.3

Type RM Length L Ch R = 1 ,102     ,,,
BEGIN DESCRIPTION:
structure xs 1
END DESCRIPTION:
XS GIS Cut Line= 5
2220320.92863193514503.403215171 2220152.0177434514541.678211874
2219910.07318708514768.332591775 2219849.9321302514832.009129962
 2219642.7300623515017.285053108
#Sta/Elev= 30
       0 2737.71    15.5 2732.79    25.4 2731.13    37.7 2724.51    54.1 2714.03
    58.2 2713.32    66.4 2715.46    70.5 2715.37   127.9 2711.69     132  2711.1
   140.2 2703.57   148.4 2700.98     368 2699.17   488.4 2699.58   501.8 2702.88
   511.4 2702.33   519.1 2699.54   527.9 2699.89   546.3 2699.95   559.9 2700.76
   571.9 2703.11   618.1 2702.03   636.1 2707.08   642.1 2707.41   687.9 2707.98
   702.1  2706.9   712.7 2709.24   750.3 2708.28   852.1 2709.28   870.3 2710.41
#Mann= 10 ,-1,0
       0     .06       0     100     .07       0  213.19      .1       0
  233.19     .07       0  343.19     .05       0  383.19     .06       0
  483.19     .07       0   527.9    .045       0   546.3     .07       0
  622.31      .1       0
#XS Ineff= 2 , 0
          505.73 2704.08   574.5         2705.07
Permanent Ineff=
       F       F
Bank Sta=527.9,546.3
XS Rating Curve= 0 ,0
Exp/Cntr(USF)=0,0
Exp/Cntr=0.3,0.1
LCMann Table=0

Chan Stop Cuts=-1
Use User Specified Reach Order=0
Composite Channel Slope=5